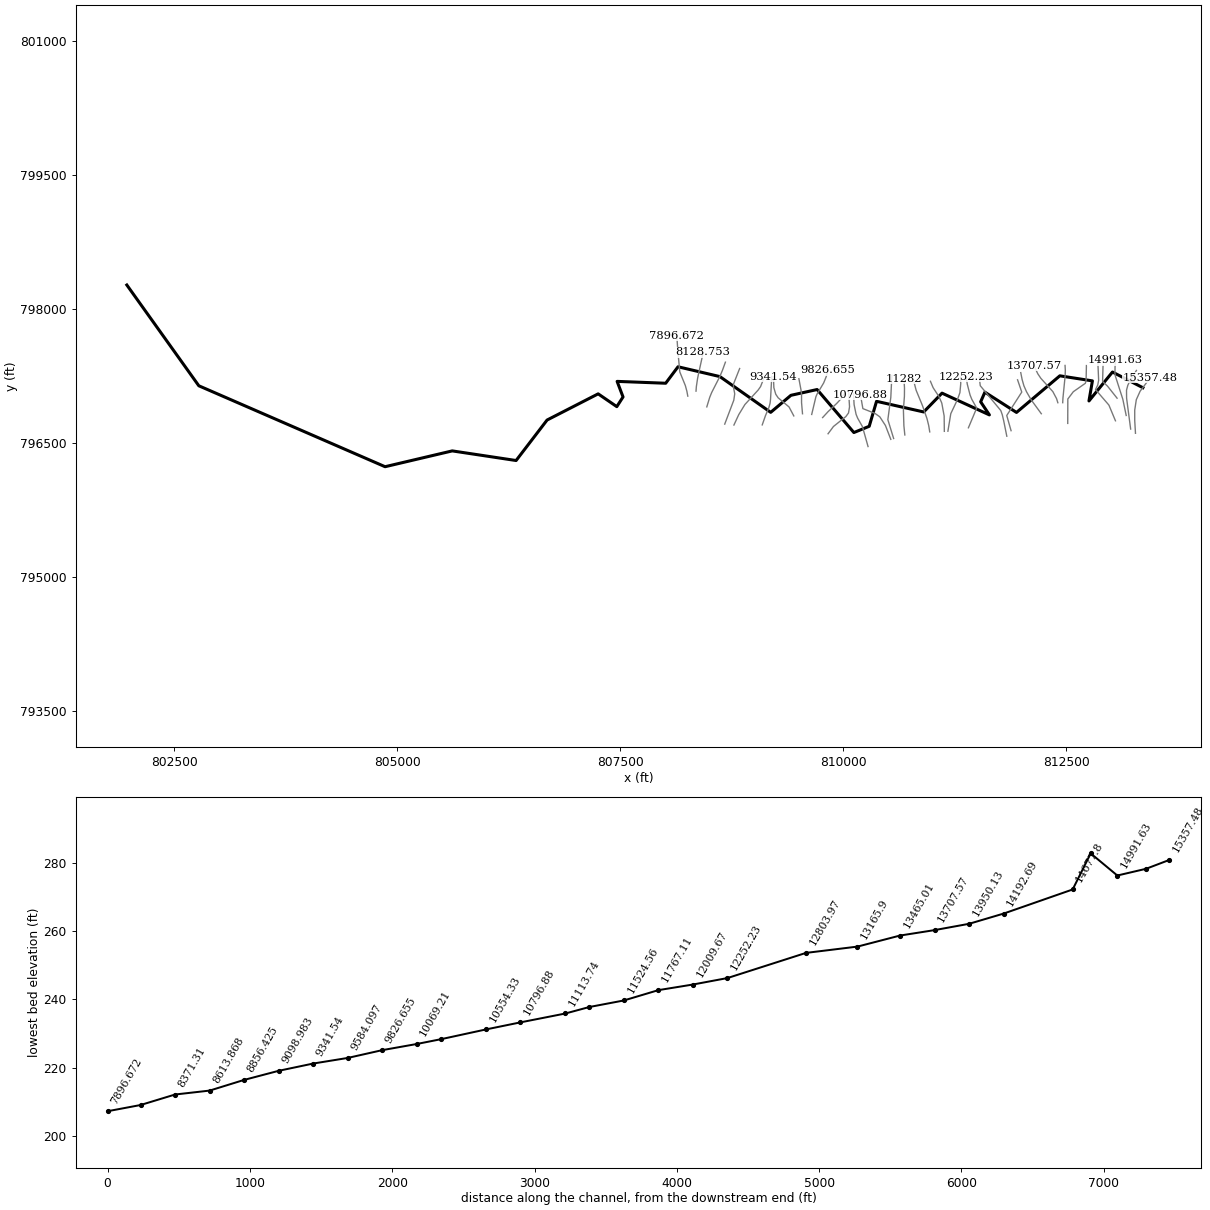
--- 17433_ras.prj (project) ---

Proj Title=17433
Current Plan=p01
Default Exp/Contr=0.3,0.1
English Units
Geom File=g01
Flow File=f01
Plan File=p01
Y Axis Title=Elevation
X Axis Title(PF)=Main Channel Distance
X Axis Title(XS)=Station
BEGIN DESCRIPTION:
RFD model 17433 exported to HEC-RAS
END DESCRIPTION:

--- 17433_ras.p01 (plan) ---

Plan Title=Plan 01
Program Version=4.10
Short Identifier=Plan 01
Geom File=g01
Flow File=f01
Subcritical Flow
Calc Critical at every XS
Secant Critical Depth

--- 17433_ras.f01 (steady flow) ---

Flow Title=Flow 01
Program Version=5.01
Number of Profiles= 6
Profile Names=10yr,25yr,50yr,100yr,100plus,500yr
River Rch & RM=17433,45,15357.48
  926.63 1482.43 2004.03 2475.18 3613.76 4914.96
River Rch & RM=17433,45,15193.53
  971.68 1555.87 2104.59 2600.64 3796.94 5133.46
River Rch & RM=17433,45,14991.63
  972.79 1557.67 2107.06 2603.72 3801.43 5138.78
River Rch & RM=17433,45,14804.56
  973.63 1559.02 2108.91 2606.02 3804.79 5142.76
River Rch & RM=17433,45, 14677.8
  998.97 1600.15 2165.09 2675.94 3906.88 5263.08
River Rch & RM=17433,45,14192.69
 1025.38  1643.6 2224.91 2750.95 4016.39 5394.07
River Rch & RM=17433,45,13950.13
 1026.43 1645.31 2227.28 2753.93 4020.74 5399.28
River Rch & RM=17433,45,13707.57
 1072.77 1721.06 2331.21  2883.8 4210.35 5622.91
River Rch & RM=17433,45,13465.01
 1078.44 1730.41 2344.12 2900.02 4234.02  5651.1
River Rch & RM=17433,45, 13165.9
 1085.13 1741.45 2359.35 2919.16 4261.97 5684.34
River Rch & RM=17433,45,12803.97
 1086.93 1744.42 2363.45 2924.31 4269.49 5693.28
River Rch & RM=17433,45,12252.23
  1133.5 1821.62  2470.3 3058.87 4465.96  5927.5
River Rch & RM=17433,45,12009.67
 1170.06  1881.7 2553.02 3162.56 4617.34 6104.85
River Rch & RM=17433,45,11767.11
 1172.77 1886.19 2559.25 3170.43 4628.83  6118.5
River Rch & RM=17433,45,11524.56
 1177.43 1893.95 2570.02 3184.01 4648.66 6142.05
River Rch & RM=17433,45,   11282
  1192.8 1919.43  2605.3 3228.45 4713.54 6218.67
River Rch & RM=17433,45,11113.74
 1202.59 1935.72 2627.89 3256.95 4755.15  6267.9
River Rch & RM=17433,45,10796.88
 1210.89 1949.52 2647.03 3281.12 4790.43 6309.63
River Rch & RM=17433,45,10554.33
 1214.06 1954.79 2654.35 3290.35 4803.91 6325.56
River Rch & RM=17433,45,10241.24
 1259.43 2030.38 2759.33 3422.95 4997.51 6554.16
River Rch & RM=17433,45,10069.21
 1261.12 2033.19 2763.23 3427.88  5004.7 6562.61
River Rch & RM=17433,45,9826.655
 1266.65  2042.4 2776.02 3444.03 5028.28 6590.35
River Rch & RM=17433,45,9584.097
 1269.98 2047.96 2783.76 3453.82 5042.57 6607.21
River Rch & RM=17433,45, 9341.54
 1273.54 2053.92 2792.04  3464.3 5057.87 6625.25
River Rch & RM=17433,45,9098.983
 1300.34 2098.67  2854.3 3543.03 5172.83 6760.59
River Rch & RM=17433,45,8856.425
 1302.94 2103.02 2860.34 3550.68 5183.99 6773.71
River Rch & RM=17433,45,8613.868
 1395.49 2256.09    3072 3816.97 5572.77 7222.12
River Rch & RM=17433,45, 8371.31
 1427.01 2308.43 3144.58 3908.49 5706.39 7376.08
River Rch & RM=17433,45,8128.753
 1440.38  2330.8 3175.72  3947.9 5763.94 7442.82
River Rch & RM=17433,45,7896.672
 1488.03 2410.18 3286.01 4087.23 5967.35 7676.88
River Rch & RM=17433,45,7643.639
  1492.1    2417 3295.53  4099.3 5984.98  7697.3
River Rch & RM=17433,45,7401.081
 1495.49 2422.69 3303.46 4109.36 5999.67 7714.29
River Rch & RM=17433,45,7267.248
  1498.2 2427.23 3309.81 4117.41 6011.41 7727.88
River Rch & RM=17433,45, 6769.54
  1522.5 2468.03 3366.73  4189.6 6116.82 7849.75
River Rch & RM=17433,45,6434.681
 1528.13 2477.46 3379.89 4206.29 6141.18 7877.86
River Rch & RM=17433,45,6271.832
 1532.17 2484.24 3389.36 4218.29  6158.7 7898.07
River Rch & RM=17433,45,6022.978
 1545.55 2506.72 3420.76 4258.15  6216.9 7965.29
River Rch & RM=17433,45,5774.124
 1557.52 2526.86 3448.92 4293.91 6269.11  8025.6
River Rch & RM=17433,45, 5525.27
 1559.74 2530.59 3454.13 4300.53 6278.77 8036.75
River Rch & RM=17433,45,5427.674
 1560.85 2532.46 3456.73 4303.84  6283.6 8042.33
River Rch & RM=17433,45,5027.562
 1562.17 2534.69 3459.85  4307.8 6289.39 8049.01
Boundary for River Rch & Prof#=17433,45,1
Up Type= 0
Dn Type= 2
Boundary for River Rch & Prof#=17433,45,2
Up Type= 0
Dn Type= 2
Boundary for River Rch & Prof#=17433,45,2
Up Type= 0
Dn Type= 2
Boundary for River Rch & Prof#=17433,45,2
Up Type= 0
Dn Type= 2
Boundary for River Rch & Prof#=17433,45,2
Up Type= 0
Dn Type= 2
Boundary for River Rch & Prof#=17433,45,2
Up Type= 0
Dn Type= 2

--- 17433_ras.g01 (geometry) ---

Geom Title=17433
Program Version=4.10

River Reach=17433,45
Reach XY= 30
813360.580181539797117.056139365813019.324873179797292.669469491
812755.727076173796968.816834509812794.386856765797193.541453436
812429.065702021797250.232134685811943.079643667796840.181215733
811588.635840386797066.923208281811541.153998435796959.009931192
811639.096971869796812.617881298811107.719330728797056.223154157
810902.494534135796845.596846998 810373.53233996796964.765305921
810291.260696948 796684.96956569810119.304800719796615.120921493
809706.913282454797096.726723731809413.288494706797031.898824513
809186.472592711796841.300279632808616.678745419 797241.57010527
808147.099990845797351.635705739808008.666781217 797167.12739259
 807463.98217994797187.870065659807530.460153848797013.660276368
 807460.56472072796905.065449759807251.462496161797048.254295841
806678.558645338 796755.08554107806331.109724104796301.822446033
805615.186031848796409.590517819804861.713809609796232.507184491
802772.902417749797138.690109998801965.532913655798267.059566408

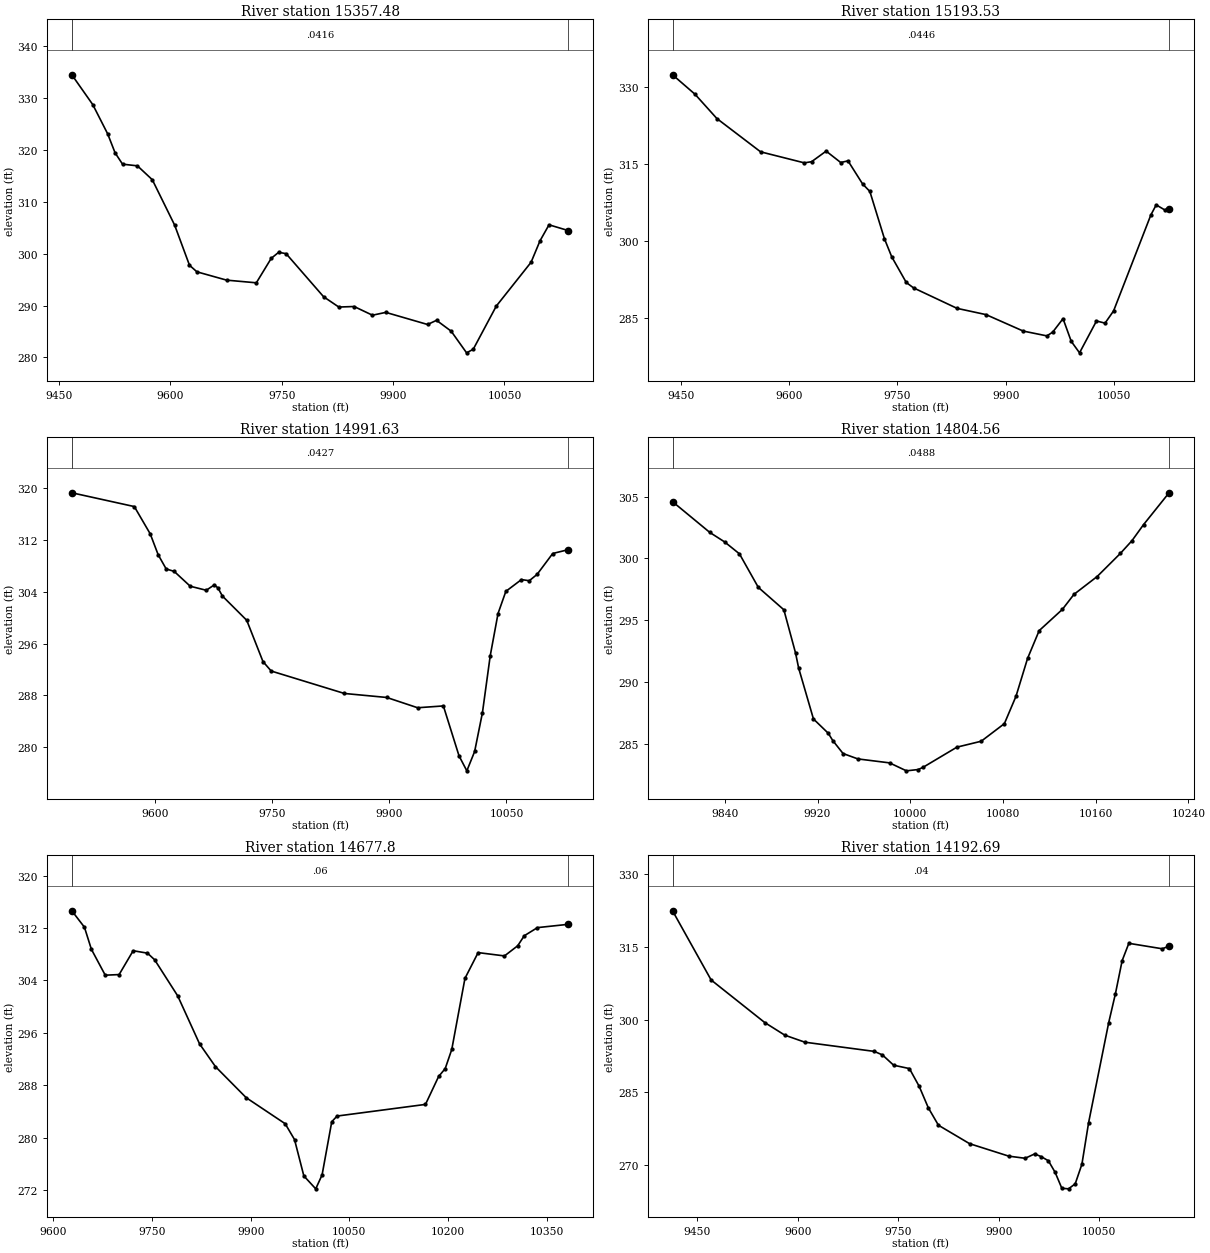
Type RM Length L Ch R = 1 ,15357.48,163.950100,163.950100,163.950100
XS GIS Cut Line= 6
813277.463348942 796606.78305906813268.991463827796749.165737502
813268.892152903796865.730534847813286.650513282796982.732164786
813329.436506664797078.044242348813441.216032836797226.603901483
#Sta/Elev= 30
9467.363334.4878 9495.63328.72849515.665323.09719525.683319.42949535.701 317.256
9555.736316.93119575.771314.25489605.824305.51379625.836297.77019635.838296.5007
9675.847294.89679715.858294.38269735.894299.0938 9745.93300.26789755.965299.9998
 9806.44291.69529826.915289.71119847.541289.81249872.255288.13589890.193288.6818
9946.471286.34589958.519287.15039978.207285.0623    9999280.882210007.96281.5718
10039.01289.896810085.85298.344910097.95302.501310110.01305.563710136.06304.4499
#Mann= 3 , 0 , 0
9467.363  0.0416       09467.363  0.0416       010136.06  0.0416       0
#XS Ineff= 2 , 0
       0                               0
Bank Sta=9467.363,10136.06
Exp/Cntr=0.3,0.1

Type RM Length L Ch R = 1 ,15193.53,201.901900,201.901900,201.901900
XS GIS Cut Line= 6
813223.208657956 796654.09167898 813177.69968589797000.540827017
813176.982765863797089.567901206 813191.33034265797143.838959013
813208.024234466797178.552936196813287.896517933797310.331579845
#Sta/Elev= 30
9438.535332.43869469.709 328.6439499.967323.91459560.482317.43149620.998315.2823
9631.084315.50689651.256317.56979671.427315.34849681.513 315.6739701.685311.1829
9711.771309.71339731.943300.50919742.029296.9906  9762.2291.97989772.286290.9285
9832.511286.94279872.576285.72469924.138 282.5179956.886281.58069964.947282.3127
9979.254284.93629990.623280.514210002.09278.278910025.57284.484710037.41284.0644
10049.25286.448910100.85305.135110108.23307.095510119.87306.132610126.07 306.362
#Mann= 3 , 0 , 0
9438.535  0.0446       09438.535  0.0446       010126.07  0.0446       0
#XS Ineff= 2 , 0
       0                               0
Bank Sta=9438.535,10126.07
Exp/Cntr=0.3,0.1

Type RM Length L Ch R = 1 ,14991.63,187.068100,187.068100,187.068100
XS GIS Cut Line= 6
813173.372081479 796806.18451613813135.507305032796987.725144017
813050.094233341797253.445883803813047.244862647797283.500993463
813048.396998178797354.545079726813053.936583703797424.926019386
#Sta/Elev= 30
9492.695319.31219572.851317.17839593.249312.95579603.448309.72139613.681307.5325
9623.969307.15349644.544304.85719665.118304.23469675.406305.07139680.048304.5987
9685.778303.34199716.989299.58959737.796293.20779748.362291.74369842.182288.2745
9896.496287.65579936.069286.06649969.092286.34729989.175278.62139999.178276.3087
10009.18279.299710019.18285.302410029.18294.118810039.18300.639710049.18304.0636
10069.21305.888110079.23305.709310089.25306.690310109.29309.921310129.35 310.519
#Mann= 3 , 0 , 0
9492.695  0.0427       09492.695  0.0427       010129.35  0.0427       0
#XS Ineff= 2 , 0
       0                               0
Bank Sta=9492.695,10129.35
Exp/Cntr=0.3,0.1

Type RM Length L Ch R = 1 ,14804.56,126.761000,126.761000,126.761000
XS GIS Cut Line= 4
  813071.0666475796999.793131456 812963.87605992 797134.62760745
812908.588283151 797187.09457925812913.665732056797367.061934203
#Sta/Elev= 30
9794.862304.59239827.064302.09879839.839301.33049852.614300.36629868.889297.6513
9890.939295.83489901.028292.33639903.714291.11299916.489286.98949929.263285.8334
9933.167285.24039942.038284.19029954.813283.75479982.181283.43379996.708282.7888
10006.92282.894910011.24283.083710040.29284.707410061.25285.186610081.25 286.612
10091.26 288.82610101.26291.896710111.27294.146510131.27 295.86410141.28297.0822
10161.29298.526910181.29300.3952 10191.3301.4259 10201.3302.727210223.37305.3119
#Mann= 3 , 0 , 0
9794.862  0.0488       09794.862  0.0488       010223.37  0.0488       0
#XS Ineff= 2 , 0
       0                               0
Bank Sta=9794.862,10223.37
Exp/Cntr=0.3,0.1

Type RM Length L Ch R = 1 , 14677.8,485.114700,485.114700,485.114700
XS GIS Cut Line= 6
813052.909483597796746.615099589812979.374638244796922.483227807
 812829.19604905797096.288397311812853.971777345797146.185222241
812864.356102312797199.888324458812854.607294711797421.972992874
#Sta/Elev= 30
9628.054314.62589647.248312.12289657.798 308.7619678.898304.80319699.999304.8948
9721.366308.53379743.103308.16219753.978307.15859789.146 301.6399822.355294.3239
9846.493290.85779893.267286.11799952.516282.15059966.724279.73699980.933274.1857
    9999 272.21710008.67274.341410023.36282.450210031.44283.317910165.89285.0942
10185.89 289.35310195.89290.553610205.89293.481910225.92304.312910245.97308.2474
10286.06  307.74 10306.1309.285810316.12310.815810336.17 312.05710383.19 312.561
#Mann= 3 , 0 , 0
9628.054    0.06       09628.054    0.06       010383.19    0.06       0
#XS Ineff= 2 , 0
       0                               0
Bank Sta=9628.054,10383.19
Exp/Cntr=0.3,0.1

Type RM Length L Ch R = 1 ,14192.69,242.557300,242.557300,242.557300
XS GIS Cut Line= 6
812517.735529006796717.347194731812518.693206698796990.779476717
812580.428899884797072.309454679812715.601586878797166.747553065
812723.590899318797199.163599089812727.213125497797365.003370702
#Sta/Elev= 30
9412.799322.42829470.453308.17539550.453299.41329580.453  296.819610.453295.3576
9714.187293.46019726.297292.73259743.011290.61669766.571289.92349781.148286.2714
9794.822281.83489809.916278.25229856.419274.45479914.973271.88379939.381271.4458
9953.691272.35059963.492 271.7789974.109270.93199984.149268.5574 9994.17 265.271
10004.18265.150910014.18266.185110024.18270.229610034.19278.803910064.21299.4087
10074.22305.343610084.24312.147910094.25315.725610144.32314.597710154.34315.1653
#Mann= 3 , 0 , 0
9412.799    0.04       09412.799    0.04       010154.34    0.04       0
#XS Ineff= 2 , 0
       0                               0
Bank Sta=9412.799,10154.34
Exp/Cntr=0.3,0.1

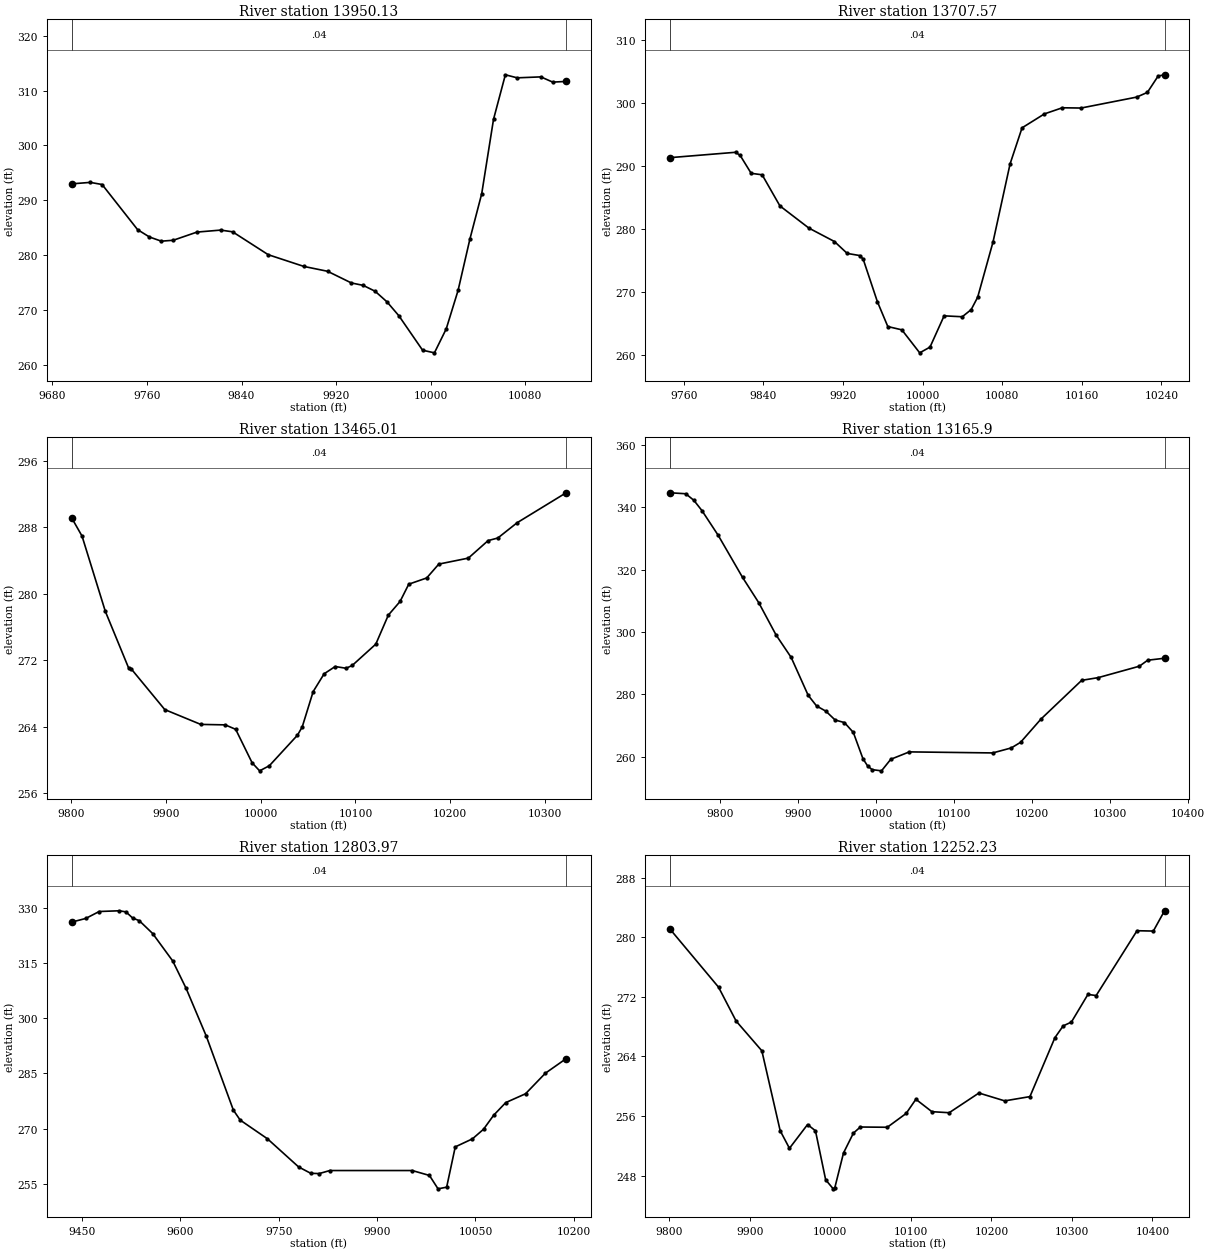
Type RM Length L Ch R = 1 ,13950.13,242.557300,242.557300,242.557300
XS GIS Cut Line= 6
812461.210043493796949.319197269812464.319724845797004.111445273
812488.321395905 797245.79675776 812488.64866704797250.764357813
812490.536422926797313.480364261812487.590885717797366.357981582
#Sta/Elev= 30
9696.267292.99279711.973293.26049721.989292.8734 9752.04284.6346 9762.09283.2907
9772.139282.53159782.188282.69919802.286284.19089822.385284.55529832.434  284.24
9862.581 280.0649892.729277.92489912.827277.03589932.926274.91069942.975274.4645
9953.024 273.3959963.073271.46489973.123268.92689993.221262.634410003.24262.1538
10013.24266.530710023.25  273.5410033.25282.905210043.26291.193710053.26304.7773
10063.27312.897910073.28312.340710093.31312.513810103.33311.5611 10114.7311.6819
#Mann= 3 , 0 , 0
9696.267    0.04       09696.267    0.04       0 10114.7    0.04       0
#XS Ineff= 2 , 0
       0                               0
Bank Sta=9696.267,10114.7
Exp/Cntr=0.3,0.1

Type RM Length L Ch R = 1 ,13707.57,242.557400,242.557400,242.557400
XS GIS Cut Line= 6
812406.763485297796948.849830386812392.488124973796994.604922088
812350.757512958797073.194581128812215.748822027797222.663626047
812181.553218793797273.774381509812140.356336047797360.963816851
#Sta/Elev= 30
 9746.32291.28079812.088292.12969816.743291.62239827.763288.79169838.783288.5592
 9856.64283.62229885.743280.10189911.418277.96969924.256276.08149937.094275.7373
9940.362275.14069954.543268.43289965.046264.4772 9979.15 263.9559997.085260.3059
10007.44261.216310021.61266.176510039.87266.032210048.79267.164110055.33 269.131
10070.78277.916610087.89 290.28910099.92296.009110122.39298.221510140.37299.1932
10159.17299.150810215.05300.885610225.85301.631810236.65304.229910243.08304.4288
#Mann= 3 , 0 , 0
 9746.32    0.04       0 9746.32    0.04       010243.08    0.04       0
#XS Ineff= 2 , 0
       0                               0
Bank Sta=9746.32,10243.08
Exp/Cntr=0.3,0.1

Type RM Length L Ch R = 1 ,13465.01,299.113200,299.113200,299.113200
XS GIS Cut Line= 6
812221.354676602796825.768049449  812109.0597865796979.343450761
812056.003225821797070.606571914 812026.34450396797138.033957316
812006.221838419797208.253495029811990.916599519797285.682145058
#Sta/Elev= 30
9800.642289.13539811.533286.95579836.121277.89559860.889 271.0319863.616270.9523
9898.835266.08069936.782264.29869962.622264.24199973.644263.70539990.985259.6777
9998.883258.712710009.14259.325410038.77262.995510043.82263.991310055.38268.2481
10066.95270.386510078.62271.261910090.07271.051810096.55271.385510121.46273.9548
10134.67277.444510147.04279.084310156.22281.165310175.15281.914410187.91283.5814
10219.12 284.30410239.93286.409310250.19286.720210270.57288.559710322.24292.1612
#Mann= 3 , 0 , 0
9800.642    0.04       09800.642    0.04       010322.24    0.04       0
#XS Ineff= 2 , 0
       0                               0
Bank Sta=9800.642,10322.24
Exp/Cntr=0.3,0.1

Type RM Length L Ch R = 1 , 13165.9,361.931100,361.931100,361.931100
XS GIS Cut Line= 4
811882.318862349796635.749972522811833.707751274796805.888861403
812002.110529006797068.041639209 811954.97809419797205.463864684
#Sta/Elev= 30
9735.746344.68869755.766 344.3789766.167342.27349776.567338.96819797.367331.0413
9828.568317.55429849.368309.42449871.589 299.0539890.969291.84599912.693279.7269
9923.522276.28319935.408274.61839947.293271.77989959.179270.96469970.591 267.804
 9982.95259.35559989.093256.98039994.835255.851910006.72255.473810018.61  259.18
10042.38 261.55510149.35261.219310173.12262.8289   10185264.623310211.12272.0739
10263.35284.508810284.49285.378210337.35289.047410347.92290.962210369.56291.6031
#Mann= 3 , 0 , 0
9735.746    0.04       09735.746    0.04       010369.56    0.04       0
#XS Ineff= 2 , 0
       0                               0
Bank Sta=9735.746,10369.56
Exp/Cntr=0.3,0.1

Type RM Length L Ch R = 1 ,12803.97,551.742300,551.742300,551.742300
XS GIS Cut Line= 6
811834.395655995796573.912572336811799.264877098796747.966949708
811783.301106677796815.199798807811766.832782711796861.411419252
811536.832751215797139.222194761811524.679973453 797236.44441697
#Sta/Elev= 30
 9434.04326.16499455.553 327.1649475.956329.04729506.561329.24559516.763328.9478
9526.965327.28369537.166326.5485 9557.57 323.0599588.175315.59749608.578 308.156
9639.389295.15289680.707275.03029691.111272.32179732.674267.24169780.285259.5779
9798.777257.84919811.655257.77659827.897258.60329953.618258.60359979.876257.2677
9993.005253.624910006.13254.077910019.26265.035210045.52 267.22510062.42269.8319
10077.85 273.63710096.28277.079310126.51279.479810156.74285.066610188.43 289.032
#Mann= 3 , 0 , 0
 9434.04    0.04       0 9434.04    0.04       010188.43    0.04       0
#XS Ineff= 2 , 0
       0                               0
Bank Sta=9434.04,10188.43
Exp/Cntr=0.3,0.1

Type RM Length L Ch R = 1 ,12252.23,242.557400,242.557400,242.557400
XS GIS Cut Line= 6
 811403.77024727796668.220688994811496.518738888796889.129566445
811441.400803697796987.891188927811422.237798519797035.675343216
811391.336815109797155.724360246811377.823130847797238.784660567
#Sta/Elev= 30
9801.106281.06189861.237273.29459883.046268.75389915.001264.76559937.776254.0439
9949.289251.68659971.767 254.8729981.594254.03429994.245247.464510003.64 246.251
10005.43246.324210016.42 251.06510028.67253.7193 10037.3254.542110070.79 254.508
 10094.2256.361210106.27258.261910126.13256.599210147.61256.457410184.55259.1008
10216.56258.046710247.88258.618210278.91266.522910289.15268.1021 10299.4268.6165
10319.88272.319410330.13272.172610380.86280.864510401.12 280.81810415.03283.5384
#Mann= 3 , 0 , 0
9801.106    0.04       09801.106    0.04       010415.03    0.04       0
#XS Ineff= 2 , 0
       0                               0
Bank Sta=9801.106,10415.03
Exp/Cntr=0.3,0.1

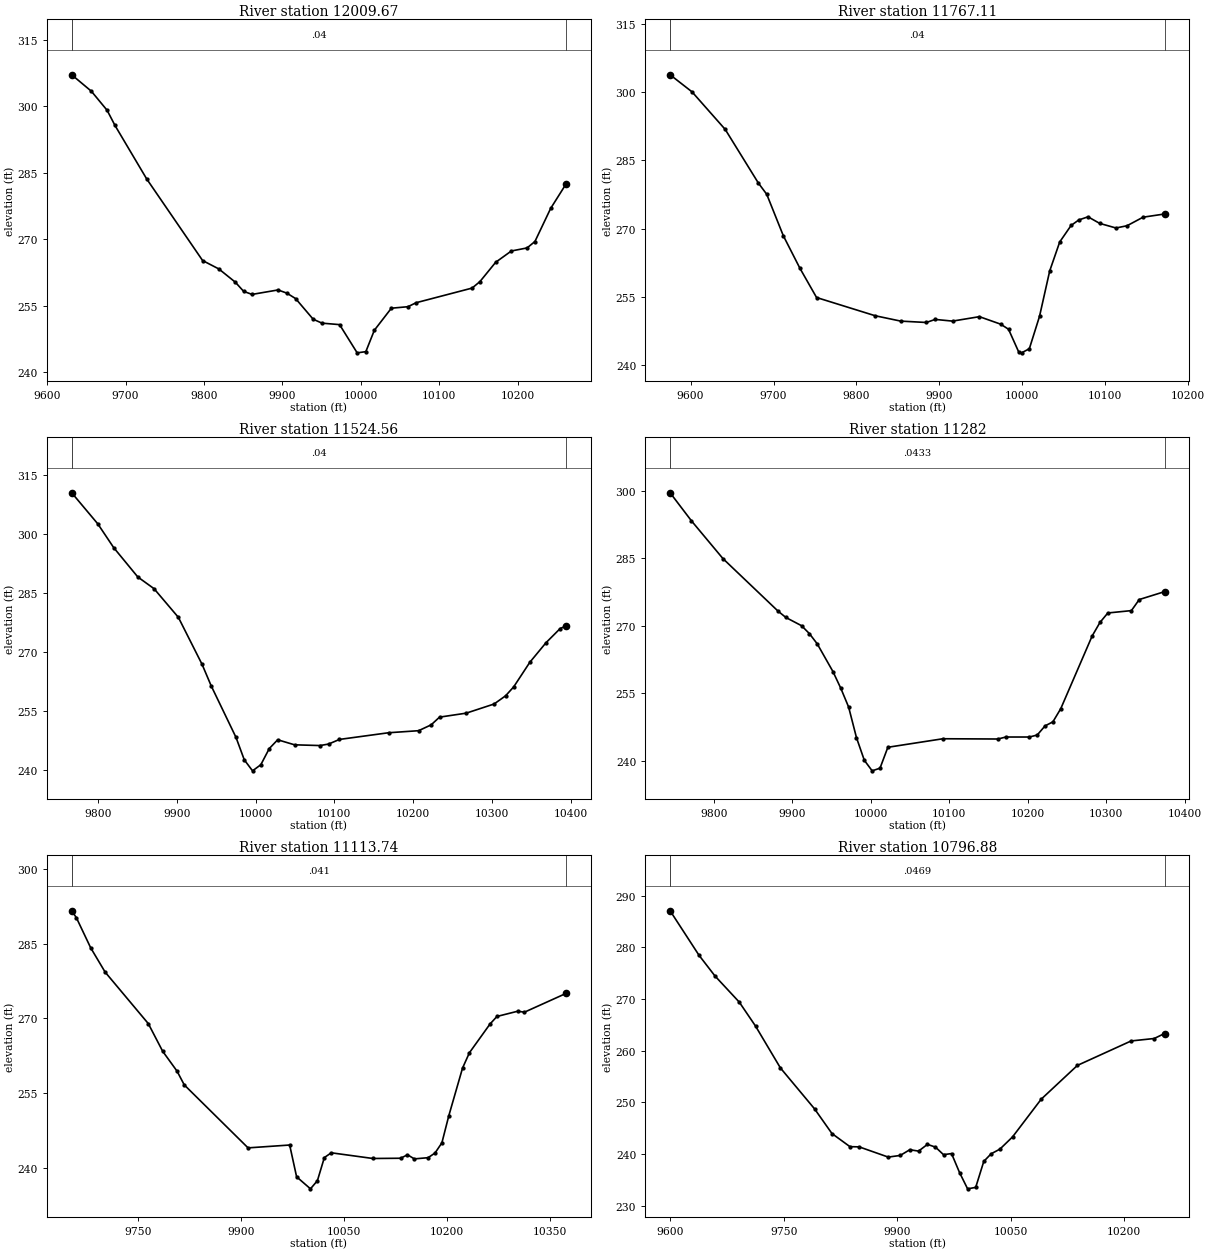
Type RM Length L Ch R = 1 ,12009.67,242.557300,242.557300,242.557300
XS GIS Cut Line= 6
811173.802007073796630.084040825811206.252293566796826.564644274
811279.567554347796981.445293356811308.411210169797061.590940235
811317.973526478797164.185519868811314.349199163797234.759484411
#Sta/Elev= 30
9631.382307.15819656.418303.44649676.514299.13959686.561295.70879726.973283.6311
9798.252265.19949818.938263.30479839.908260.31959850.588258.23689861.268257.5528
9894.367258.55919905.575257.84429916.782256.60979939.198 251.9439950.406251.0616
9972.821250.72739995.237244.3555 10006.3244.623610017.14249.454310038.83254.4346
10059.96254.775510070.41255.676610141.75258.982810151.76260.452310171.77264.8082
10191.78267.359610211.81268.050210221.82269.499810241.85276.966710261.63282.5351
#Mann= 3 , 0 , 0
9631.382    0.04       09631.382    0.04       010261.63    0.04       0
#XS Ineff= 2 , 0
       0                               0
Bank Sta=9631.382,10261.63
Exp/Cntr=0.3,0.1

Type RM Length L Ch R = 1 ,11767.11,242.557300,242.557300,242.557300
XS GIS Cut Line= 6
811133.753036863796628.555454175811131.722886126796800.410746525
811105.311979836796944.465797984811073.513397806797017.459590961
811008.135982077797117.013334404810977.901306919797189.100776181
#Sta/Elev= 30
9575.342303.7766 9601.79300.02479641.795291.77329681.812279.98029691.822277.5339
9711.841268.42149731.861261.27499751.901254.86079822.578 250.8579853.336249.6792
9884.225249.37959894.902250.05179915.766249.67969948.205250.65499973.846249.0065
9983.305247.89189995.849242.7915    9999242.711610008.38243.607310020.66 250.721
10032.94260.700410045.02267.060310058.69270.678210067.95271.891710079.14272.5853
10093.18271.1419 10112.8270.130510126.15270.6219 10145.5272.501310171.39273.2024
#Mann= 3 , 0 , 0
9575.342    0.04       09575.342    0.04       010171.39    0.04       0
#XS Ineff= 2 , 0
       0                               0
Bank Sta=9575.342,10171.39
Exp/Cntr=0.3,0.1

Type RM Length L Ch R = 1 ,11524.56,242.557400,242.557400,242.557400
XS GIS Cut Line= 6
810970.188974687796622.312551035810958.281634811796693.834402761
810939.655870963796769.561141707810888.398888221796916.836908445
810817.470224692797088.693739671810783.253695985797219.949027408
#Sta/Elev= 30
  9766.3310.53439799.437302.61849819.713296.53729850.305289.07569870.901286.0988
9901.795278.7992 9931.95266.80859943.521261.33389975.044248.20649985.552242.4882
 9996.06239.684110006.59241.2485 10017.3245.3597   10028247.599110049.41246.3162
10081.69246.127310092.59246.503210106.46 247.68810168.89249.390210207.03249.9122
10222.97251.4048 10233.6 253.36610267.53254.382910302.93256.714810317.48 258.796
 10327.8  261.0710348.33267.344110368.87272.329910386.78275.921710394.48276.6537
#Mann= 3 , 0 , 0
  9766.3    0.04       0  9766.3    0.04       010394.48    0.04       0
#XS Ineff= 2 , 0
       0                               0
Bank Sta=9766.3,10394.48
Exp/Cntr=0.3,0.1

Type RM Length L Ch R = 1 ,   11282,168.261400,168.261400,168.261400
XS GIS Cut Line= 6
  810690.6658323796587.974836965810680.130266415796692.548816402
 810674.67106508796869.527073031810686.087285946797022.239682911
 810686.95011758797114.345470374810681.065633293797217.201695844
#Sta/Elev= 30
9743.976299.57039771.215293.32799811.385284.93489881.561273.27459891.566271.8554
9911.576270.02689921.581 268.2699931.586265.99099951.596259.8361  9961.6  256.13
9971.605 251.944 9981.61245.14279991.615 240.11210001.62237.765710011.63238.3602
10021.63 243.00310091.81244.897810162.01 244.84110172.04245.281810202.06245.2832
10212.06245.727610222.06247.755810232.06248.657110242.06251.575110282.08267.7298
10292.09270.753410302.11272.855110332.16273.379610342.18275.842210374.43 277.593
#Mann= 3 , 0 , 0
9743.976  0.0433       09743.976  0.0433       010374.43  0.0433       0
#XS Ineff= 2 , 0
       0                               0
Bank Sta=9743.976,10374.43
Exp/Cntr=0.3,0.1

Type RM Length L Ch R = 1 ,11113.74,316.853200,316.853200,316.853200
XS GIS Cut Line= 4
810565.155027145796548.540698861810500.374417901796759.013861403
810533.360528976797007.277750313810545.513306797797255.541639209
#Sta/Elev= 30
9653.871291.58119660.629290.20549681.555284.14119702.481279.29789765.259268.9753
9786.184263.4324 9807.11259.44359817.573256.6975 9910.39244.07229970.917244.6444
9981.005238.276610001.18235.864310011.27237.502510021.36242.128310031.44243.0852
10091.97241.946410132.26241.993710142.28242.691310152.29 241.86410172.31 242.108
10182.32243.041410192.34245.082210202.35250.492910222.37  260.0610232.38263.1359
10262.42268.904310272.43270.405510302.47271.450710312.48271.266310373.09275.0335
#Mann= 3 , 0 , 0
9653.871   0.041       09653.871   0.041       010373.09   0.041       0
#XS Ineff= 2 , 0
       0                               0
Bank Sta=9653.871,10373.09
Exp/Cntr=0.3,0.1

Type RM Length L Ch R = 1 ,10796.88,242.557400,242.557400,242.557400
XS GIS Cut Line= 6
810533.503623824796538.596170115810473.223696615796694.113547683
810409.589385586796791.645755701810355.655822932796829.476087466
810220.143073256796883.175273156810193.082751244797038.527750313
#Sta/Elev= 30
9599.769287.05689638.054278.43789659.102274.44349691.227269.38649712.718264.7512
9745.667256.64169790.789248.72839813.791243.95399837.587241.41559849.731241.3781
9888.209239.39899904.072239.71749916.715240.82249928.306240.55589940.066241.8607
 9950.68241.32489961.301239.86779971.922240.07839982.543236.39249993.163233.2553
10003.86233.537410014.55238.564810024.22240.029210035.93240.946910052.53243.2938
10090.47250.599410138.35257.138810209.41261.870810239.86262.342310253.59263.3053
#Mann= 3 , 0 , 0
9599.769  0.0469       09599.769  0.0469       010253.59  0.0469       0
#XS Ineff= 2 , 0
       0                               0
Bank Sta=9599.769,10253.59
Exp/Cntr=0.3,0.1

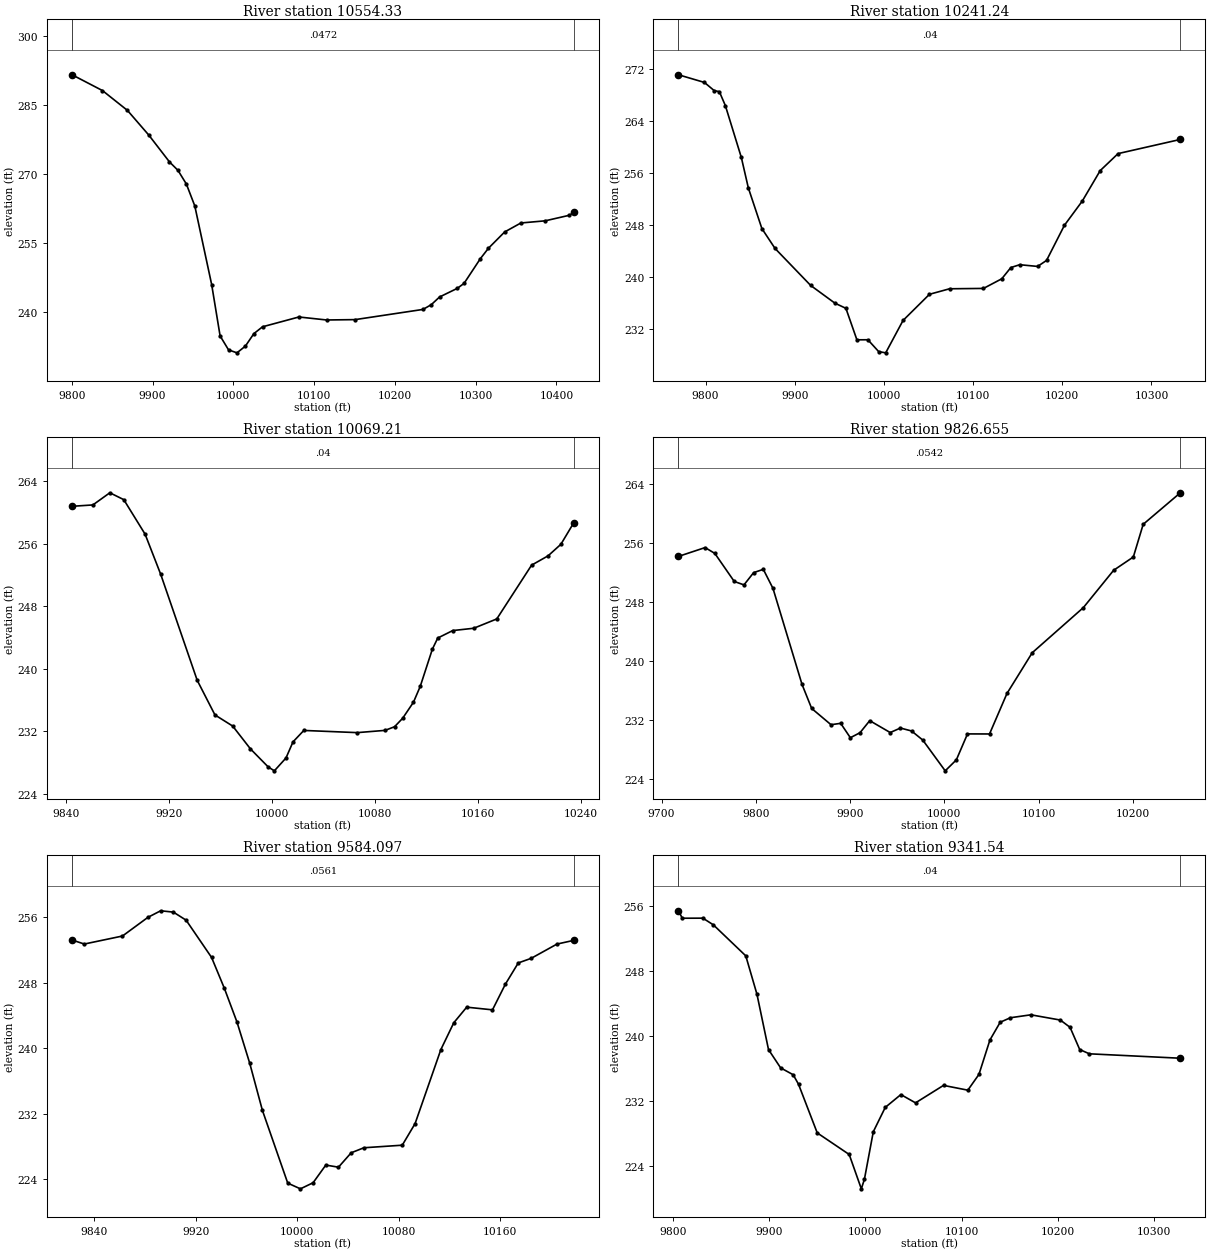
Type RM Length L Ch R = 1 ,10554.33,313.081900,313.081900,313.081900
XS GIS Cut Line= 6
810278.135718007796458.362334845810215.594107939 796680.76382144
810161.707838892796775.796101185810144.204118793796818.616327817
 810121.78117855796927.211531329810115.194513397 797050.60751397
#Sta/Elev= 30
9800.304291.63159837.954288.19669868.851283.88929895.366278.5083 9920.93272.6864
9931.377270.86469941.823267.8862 9952.27263.11879973.164246.02049983.611234.8569
9994.058231.826410004.48231.180710014.94232.6458 10025.4235.352910036.12236.8414
 10081.2238.975610115.44238.325310150.77238.402810234.86  240.6210245.16241.6594
10255.34243.321810277.39245.206310285.71246.286610305.89251.656910315.92253.9254
10335.99 257.46410356.06259.411710386.12  259.8810416.12261.089210421.73261.7364
#Mann= 3 , 0 , 0
9800.304  0.0472       09800.304  0.0472       010421.73  0.0472       0
#XS Ineff= 2 , 0
       0                               0
Bank Sta=9800.304,10421.73
Exp/Cntr=0.3,0.1

Type RM Length L Ch R = 1 ,10241.24,172.032700,172.032700,172.032700
XS GIS Cut Line= 6
809829.739697479796601.433443102809890.485683356796682.949617826
810029.439546174796794.075465556810059.214161742796834.322339979
810070.541752444796903.343298379810060.776736673797064.674694352
#Sta/Elev= 30
9769.636271.13539798.699269.95849809.677268.69979815.462268.54049822.214266.3902
9840.133258.40619847.929 253.7459863.154247.47119877.902244.41059917.841238.7203
9945.043235.9889 9957.37235.19589969.697230.35089982.025230.35669994.121228.5356
10001.98228.345410021.43233.326910051.06 237.35510073.59238.202910111.63 238.258
10132.14239.742510142.29241.4695 10152.3241.907310172.31241.643210182.34242.5666
10202.39247.972710222.44251.7071 10242.5256.387710262.55259.005610332.34261.1834
#Mann= 3 , 0 , 0
9769.636    0.04       09769.636    0.04       010332.34    0.04       0
#XS Ineff= 2 , 0
       0                               0
Bank Sta=9769.636,10332.34
Exp/Cntr=0.3,0.1

Type RM Length L Ch R = 1 ,10069.21,242.557400,242.557400,242.557400
XS GIS Cut Line= 6
809768.800393132 796782.72253684809828.936398643796847.989216918
809929.641830089796943.885728182809967.354147929 796984.43614728
810001.962106927797032.190424807810023.947842137797074.195088861
#Sta/Elev= 30
 9844.94260.79669861.099260.9695 9874.27262.52719885.092261.64649901.643257.2271
9913.758252.09299942.094238.51829955.883234.08099969.673232.65399983.463 229.729
9997.252227.418410002.01226.922210011.06228.571810016.49230.629110024.89 232.095
10066.37231.814810087.97232.103510095.34232.569110101.63233.652510110.03235.7102
10115.28237.732810124.71242.502710128.89243.927710140.51244.883110156.83245.1795
10174.73246.374110201.75253.259110214.58254.455210224.49255.928710234.62258.7198
#Mann= 3 , 0 , 0
 9844.94    0.04       0 9844.94    0.04       010234.62    0.04       0
#XS Ineff= 2 , 0
       0                               0
Bank Sta=9844.94,10234.62
Exp/Cntr=0.3,0.1

Type RM Length L Ch R = 1 ,9826.655,242.557300,242.557300,242.557300
XS GIS Cut Line= 6
809646.289063401 796817.59114608809692.979473857797014.255814452
809706.368707952 797045.86744999809780.578496901797170.682529455
809807.633667669797237.070310103809830.436819631 797312.74613779
#Sta/Elev= 30
9717.962254.22929746.227255.42789756.539254.63469777.164 250.8259787.464 250.364
9797.726 252.0289807.987252.47289818.249 249.8849849.034236.86489859.296233.5912
9879.819231.38099890.081231.56919900.342229.61489910.604230.2969 9920.91231.9324
 9942.63230.3195 9953.49230.92959965.302230.53149977.204229.2949   10001225.1196
10012.83226.610110024.65 230.13310048.03230.124310066.54235.621410093.32241.1483
10147.61247.280810179.73252.345910200.63254.149710211.08258.583910250.49262.8666
#Mann= 3 , 0 , 0
9717.962  0.0542       09717.962  0.0542       010250.49  0.0542       0
#XS Ineff= 2 , 0
       0                               0
Bank Sta=9717.962,10250.49
Exp/Cntr=0.3,0.1

Type RM Length L Ch R = 1 ,9584.097,242.557300,242.557300,242.557300
XS GIS Cut Line= 6
 809543.25062376796825.397224162809532.560562662796949.008258112
809532.381822267797031.217092629809530.987724596797057.321714787
809526.115478384797092.395294375809502.682514383797218.122509929
#Sta/Elev= 30
9822.383  253.249832.022 252.7489862.134253.72759882.209256.01069892.246256.8115
9902.283256.64819912.321255.66139932.395251.10899942.433247.35329952.448243.2081
9962.448238.19799972.449232.4355 9992.45223.535310002.45222.835810012.46 223.582
10022.46225.738510032.46225.482210042.48227.240310052.49227.854710082.76228.1681
10092.88 230.81110113.22239.860710123.39243.128510133.57 245.03410153.91244.7074
10164.08247.846210174.25250.440210184.43251.001310204.77252.744810218.12253.2006
#Mann= 3 , 0 , 0
9822.383  0.0561       09822.383  0.0561       010218.12  0.0561       0
#XS Ineff= 2 , 0
       0                               0
Bank Sta=9822.383,10218.12
Exp/Cntr=0.3,0.1

Type RM Length L Ch R = 1 , 9341.54,242.557400,242.557400,242.557400
XS GIS Cut Line= 6
809445.492770305796801.220550728809392.337885632796901.469272841
809270.161190049797004.030104338809243.160580949797043.803300958
809221.795011813 797118.12240743809217.437961201797239.384942914
#Sta/Elev= 30
9805.863255.4617 9809.81254.54399831.228254.55239842.136253.72379875.769249.9078
9887.363245.18499899.378238.35819911.946236.10589925.031235.25239930.537234.0892
9949.992228.08849983.195225.42899995.794221.1946    9999222.375110008.22228.2297
10020.64231.229510036.85232.8111 10052.1231.790710081.15233.943710106.41 233.354
10117.95235.294910129.38239.541610140.04241.726910150.69242.281210171.92242.6416
 10202.5241.994310212.59 241.10110222.63238.361410232.68237.834510327.13237.2904
#Mann= 3 , 0 , 0
9805.863    0.04       09805.863    0.04       010327.13    0.04       0
#XS Ineff= 2 , 0
       0                               0
Bank Sta=9805.863,10327.13
Exp/Cntr=0.3,0.1

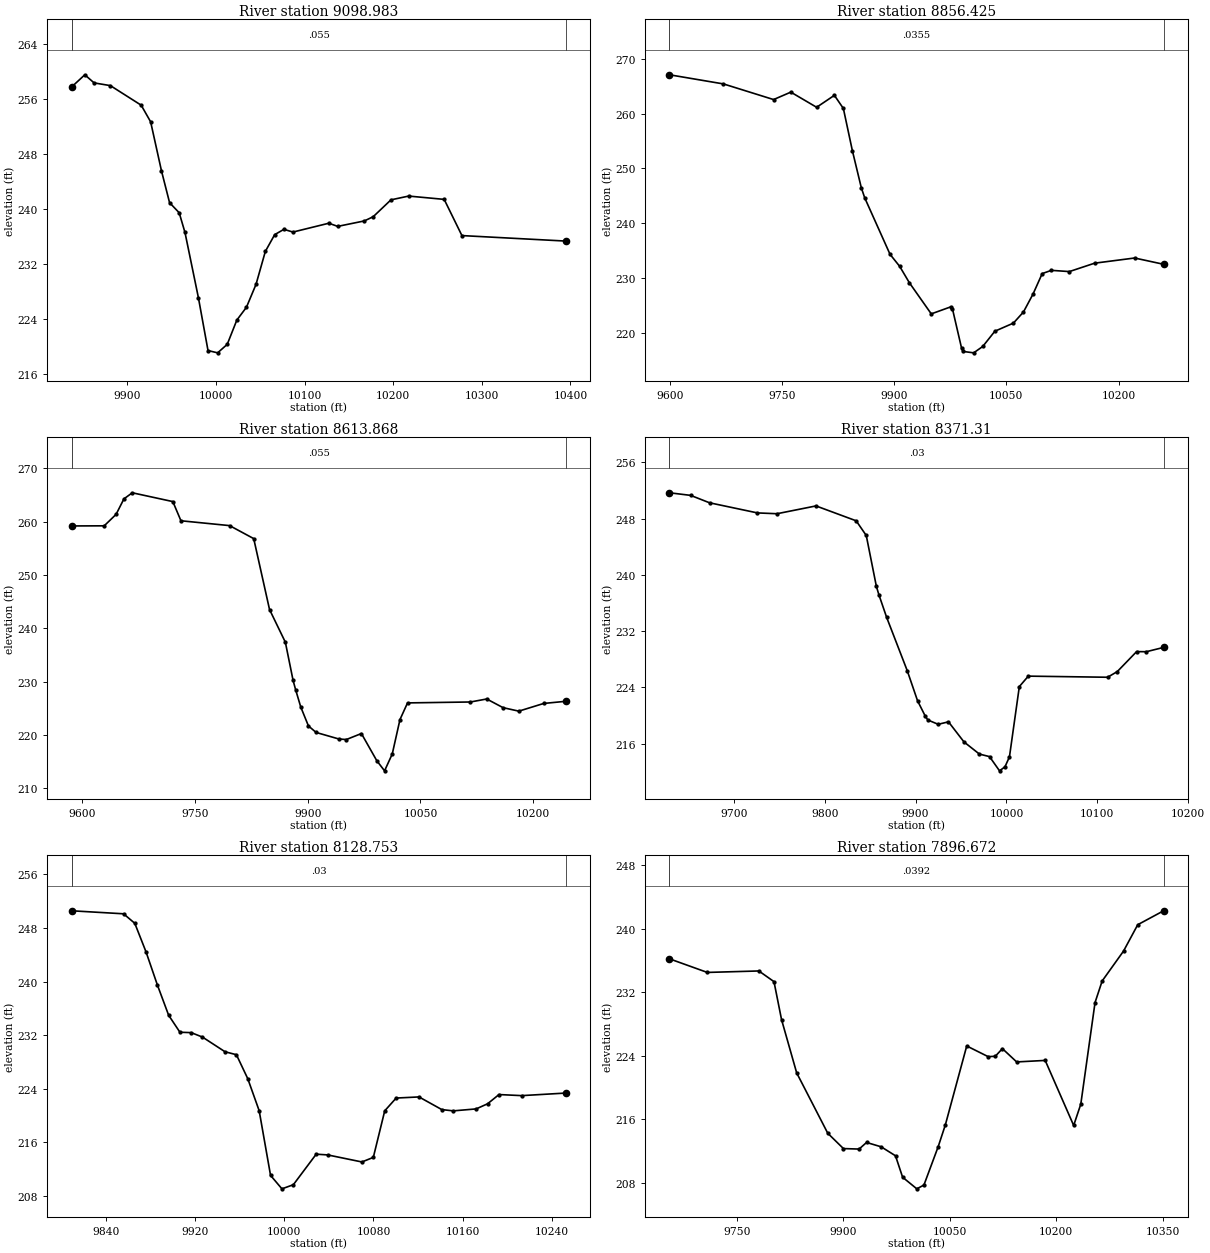
Type RM Length L Ch R = 1 ,9098.983,242.557300,242.557300,242.557300
XS GIS Cut Line= 6
809091.520967534796700.707657616809127.299993896796802.692622441
809166.117101121796895.378784391  809179.6902576796944.442950076
809184.655534098796988.492699634809198.411010349797241.890270962
#Sta/Elev= 30
9836.974257.77969851.936259.56379862.404258.3804 9880.77257.98559915.563 255.132
9926.224252.71079938.453245.5689 9947.59240.93489958.436239.46799964.971236.5973
9980.128 227.0959990.975219.396510001.83219.064310012.66220.2999 10023.5223.8337
10034.33225.698810045.16229.040210055.69233.8424 10066.2236.278310076.62237.0513
10086.86236.655210127.29237.941910137.35237.4828 10167.4238.277510177.41238.8935
10197.44 241.34710217.46241.8973 10257.5241.416510277.53236.143210394.65235.3433
#Mann= 3 , 0 , 0
9836.974   0.055       09836.974   0.055       010394.65   0.055       0
#XS Ineff= 2 , 0
       0                               0
Bank Sta=9836.974,10394.65
Exp/Cntr=0.3,0.1

Type RM Length L Ch R = 1 ,8856.425,242.557300,242.557300,242.557300
XS GIS Cut Line= 6
808774.081148785796699.249805257808827.810486675796814.990348193
808897.165107334796928.759290612809045.155374533797090.352080134
809072.897694636797129.744025235809121.542800729797252.011707819
#Sta/Elev= 30
9599.654267.07139671.826265.40379738.823 262.5559761.832263.90839796.347261.1475
9820.074263.32639832.087 260.931  9844.1253.25179856.113246.46089860.629244.6444
 9894.48234.35179907.381232.15269920.281  229.189949.582223.49819976.036224.7982
9977.952224.39079990.136217.22749992.136216.654110006.27216.398210018.41217.5606
10034.59220.337510059.41221.8178 10072.8223.838610085.64227.115210097.87230.8407
10110.11231.431510134.15231.206810167.93232.736910221.43233.680110260.19 232.535
#Mann= 3 , 0 , 0
9599.654  0.0355       09599.654  0.0355       010260.19  0.0355       0
#XS Ineff= 2 , 0
       0                               0
Bank Sta=9599.654,10260.19
Exp/Cntr=0.3,0.1

Type RM Length L Ch R = 1 ,8613.868,242.557400,242.557400,242.557400
XS GIS Cut Line= 6
808670.826846255796709.382236811808772.914235502796978.133194098
808782.903549206797048.946073606808768.493582971797128.317198603
 808770.94511918 797162.22608099808838.293220579797332.169709516
#Sta/Elev= 30
9585.992259.17899629.422259.2028  9645.2261.35139655.643264.25649666.766265.3978
9720.682263.74559731.466260.14929796.165259.24229828.243256.80549849.274 243.509
9870.305237.38839880.609230.21199883.999228.46379890.816 225.2289901.024221.6821
9911.231220.46269941.324219.24419951.361 219.1329971.453220.26059991.937215.1631
10002.25213.265810012.49216.427610022.73222.874810032.81226.002210116.43226.1743
10138.13226.736610159.83225.111810180.78224.456710213.98225.901910243.15226.3009
#Mann= 3 , 0 , 0
9585.992   0.055       09585.992   0.055       010243.15   0.055       0
#XS Ineff= 2 , 0
       0                               0
Bank Sta=9585.992,10243.15
Exp/Cntr=0.3,0.1

Type RM Length L Ch R = 1 , 8371.31,242.557300,242.557300,242.557300
XS GIS Cut Line= 6
808469.826447276796902.472889347808502.873467685797010.112888422
808524.932512418797063.981734082808615.269669626797241.024659663
808645.044406401797311.075003524808678.517991435797402.913560964
#Sta/Elev= 30
9629.318251.66539652.581251.29579673.345250.24319726.049248.8017 9747.59248.6854
9790.483249.7962 9834.66247.67959845.774245.59269856.887238.36119859.627237.1771
9868.171233.9531 9890.85226.36179902.189222.08359910.822219.85879913.529219.3486
9924.868218.73679936.208219.08789953.241216.23289970.226214.50149981.346214.1423
9992.363212.11819998.357212.693710003.28214.107410014.15224.103610024.03225.5876
10111.23225.428510121.87226.231610143.16229.0765 10153.8229.059910172.87229.6734
#Mann= 3 , 0 , 0
9629.318    0.03       09629.318    0.03       010172.87    0.03       0
#XS Ineff= 2 , 0
       0                               0
Bank Sta=9629.318,10172.87
Exp/Cntr=0.3,0.1

Type RM Length L Ch R = 1 ,8128.753,232.080700,232.080700,232.080700
XS GIS Cut Line= 6
808348.951323844797078.534385795808352.588548033797128.110016549
808366.012344408797217.958837007808376.052274479797267.998148667
808418.470881494797461.182774815808428.190683195797513.751254658
#Sta/Elev= 30
9809.408250.57649855.999250.12559866.084 248.7029876.195244.41229886.306239.4994
9896.417234.96799906.528232.43129916.639232.3737 9926.75231.70699946.972229.5138
9957.145 229.0759967.345225.48559977.544220.70739987.743211.04669997.943209.0387
10008.17209.654410028.65214.216410038.88214.1078 10069.6213.053810079.84213.7362
10090.07220.693610100.31222.601210120.79 222.76810141.27220.8735 10151.5220.6872
10171.98220.978610182.22221.742510192.46223.123410212.84222.962610252.25223.3463
#Mann= 3 , 0 , 0
9809.408    0.03       09809.408    0.03       010252.25    0.03       0
#XS Ineff= 2 , 0
       0                               0
Bank Sta=9809.408,10252.25
Exp/Cntr=0.3,0.1

Type RM Length L Ch R = 1 ,7896.672,253.034000,253.034000,253.034000
XS GIS Cut Line= 6
808256.685382719797022.621963626808246.571097227797076.825153228
808229.166556675797141.254017427808167.119074587 797293.25133159
808144.939011274797531.542440878808133.319757279797701.404063847
#Sta/Elev= 30
9655.386236.19889708.668234.48589781.254234.67069802.563233.32459813.217228.5371
9834.527221.82489878.316214.21819900.364212.28899922.411212.22749932.942213.0598
 9953.54212.51099973.699211.38039983.713 208.67910003.74207.215910013.76207.6988
10033.84212.533310043.89215.269510074.02225.219310104.16223.874910114.21223.9176
10124.25224.881810144.34223.207510184.52223.398310224.63215.201710234.66217.8866
10254.72230.690910264.74 233.40710294.83237.172910314.86240.497910351.32242.2541
#Mann= 3 , 0 , 0
9655.386  0.0392       09655.386  0.0392       010351.32  0.0392       0
#XS Ineff= 2 , 0
       0                10051.12       0
Bank Sta=9655.386,10351.32
Exp/Cntr=0.3,0.1