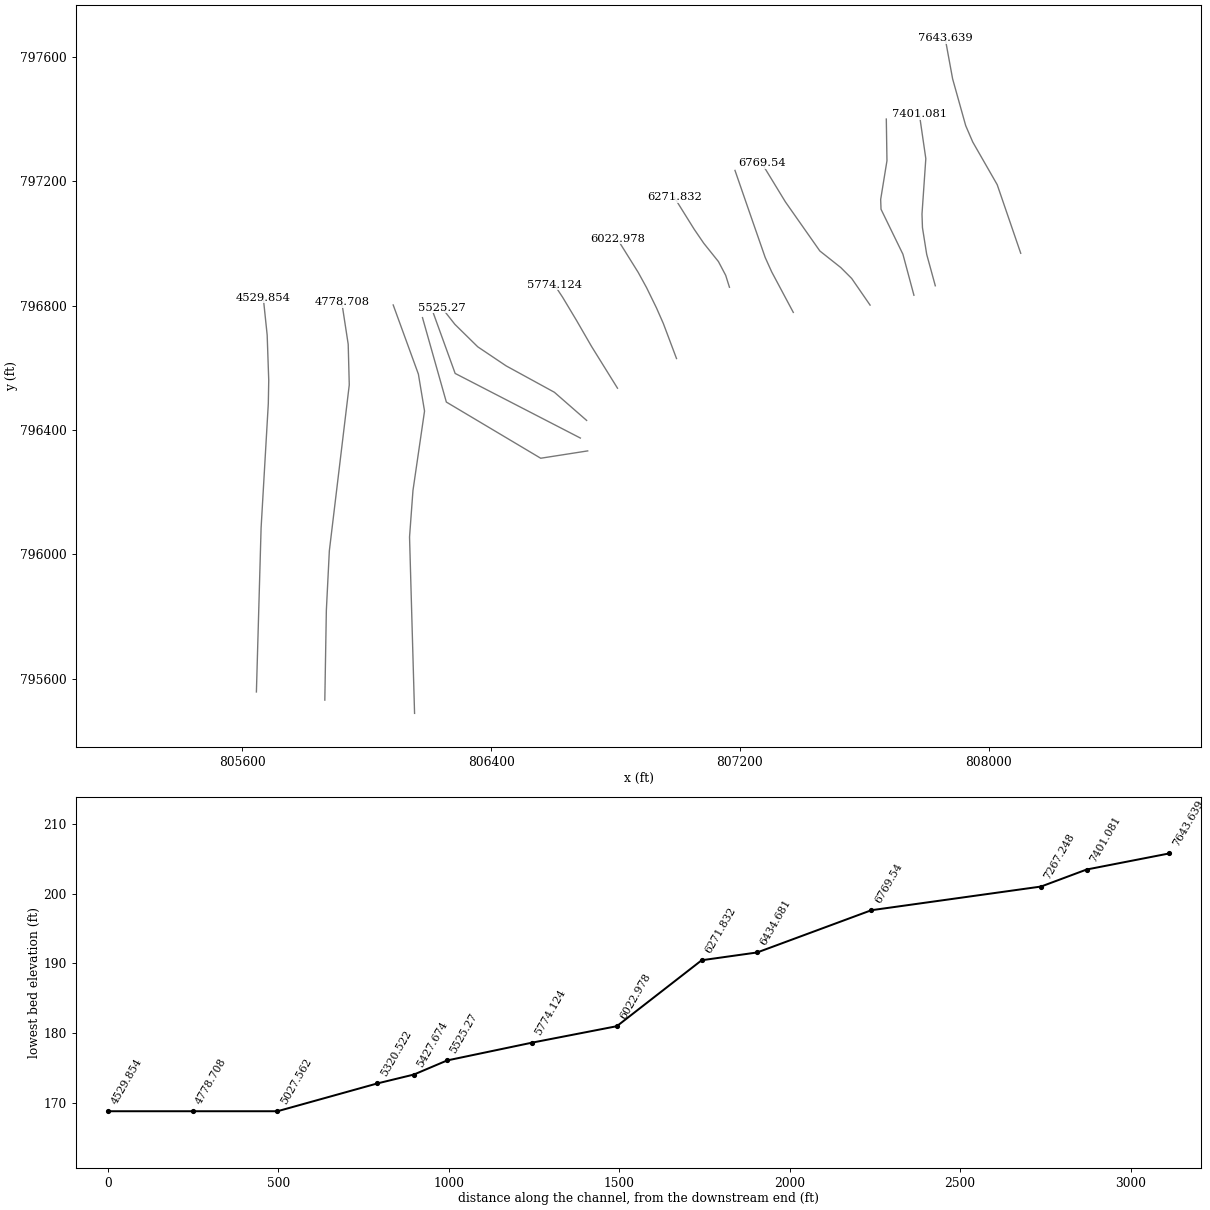
HEC-RAS study 17433_ras.prj: 17433

--- 17433_ras.g01 (geometry) --- (continued)

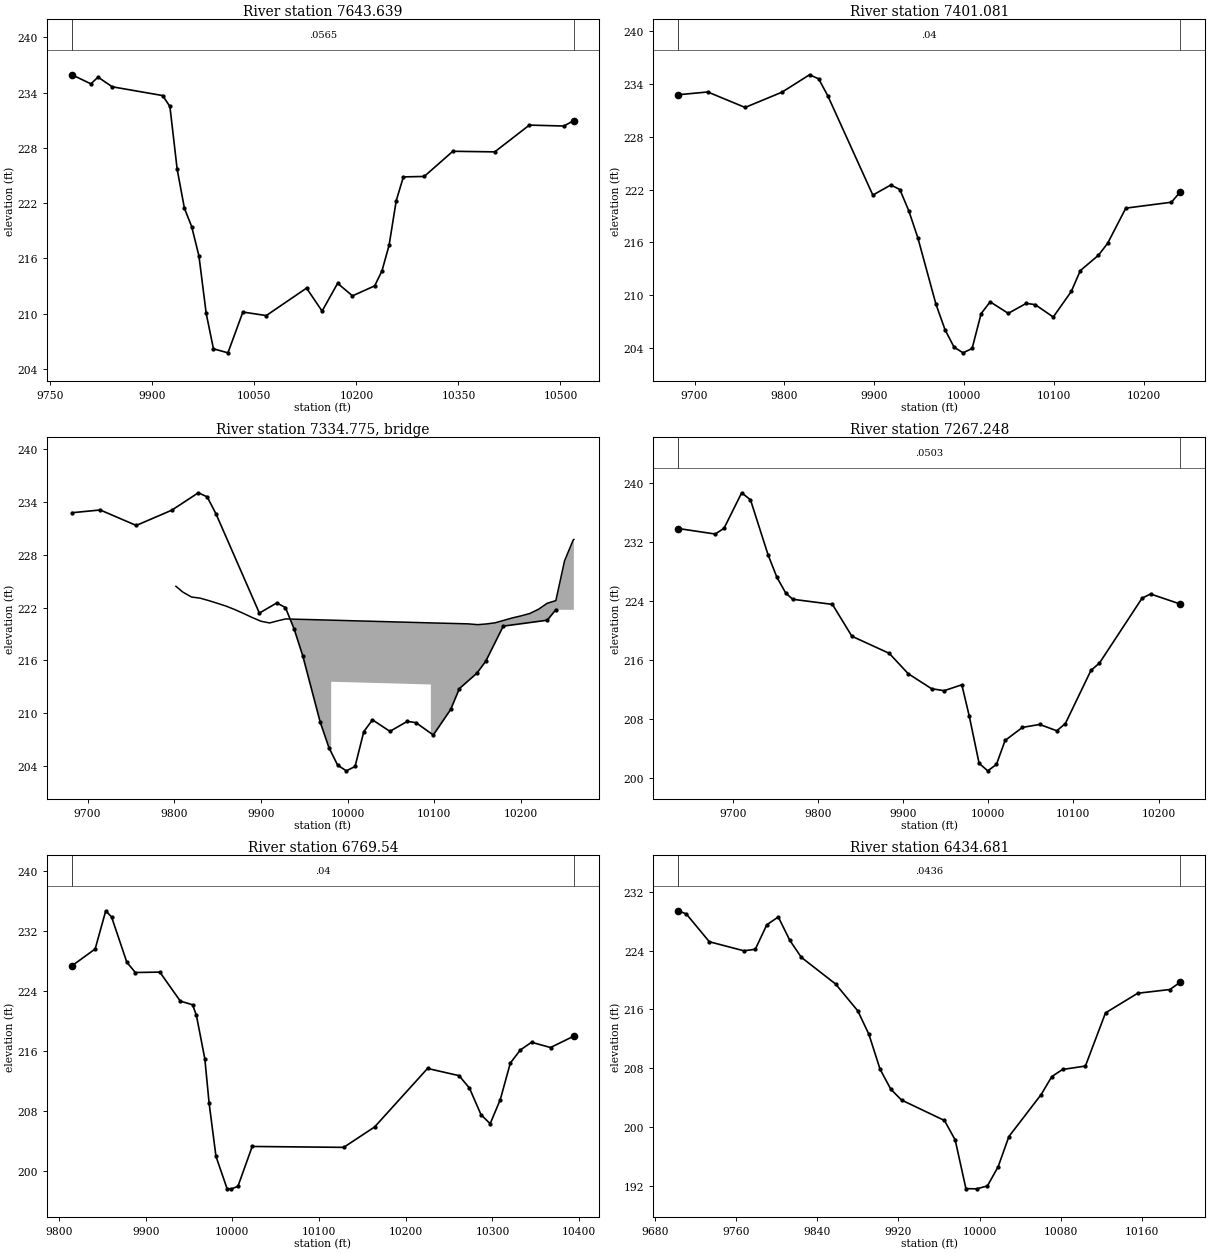
Type RM Length L Ch R = 1 ,7643.639,242.557300,242.557300,242.557300
XS GIS Cut Line= 6
808103.278851339796968.187387992808027.583374197 797188.81533229
807948.883397517797326.135814406807926.316992051797378.560052933
807884.207826137797529.135645976807860.294479379797659.401711166
#Sta/Elev= 30
9781.837235.93229809.721234.94739820.146235.68039841.008234.63039915.169233.6769
9925.838232.49299936.507225.68339947.175221.44789957.844219.46019968.512216.2795
9979.181210.0411 9989.85206.200810011.14 205.76310033.12210.189910067.48209.8062
10126.73212.786610149.55210.289910172.37213.305110194.21211.946210226.87213.0285
10237.52214.643810248.03217.427310258.55222.273110269.06224.851610299.69224.9006
10341.78227.632810403.35227.566810454.23230.472610505.08230.371310519.66230.9678
#Mann= 3 , 0 , 0
9781.837  0.0565       09781.837  0.0565       010519.66  0.0565       0
#XS Ineff= 2 , 0
       0                               0
Bank Sta=9781.837,10519.66
Exp/Cntr=0.3,0.1

Type RM Length L Ch R = 1 ,7401.081,133.833000,133.833000,133.833000
XS GIS Cut Line= 6
807828.550471586796863.683583196807800.846226461796964.875189201
807787.247302111797050.526673852807785.749948636797094.317931195
807798.039662524797272.582864984807777.393301527797414.721667968
#Sta/Elev= 30
9682.045232.79049714.649233.10269756.199231.34449797.288233.08379827.832235.0574
9837.991234.59539848.059232.68949898.247221.3835 9918.26222.53229928.273222.0179
9938.287219.5836  9948.3216.52129968.392208.99579978.458206.09729988.523204.1009
 9998.58203.453510008.63203.948710018.68207.913510028.72209.250510048.82207.9413
10068.85209.076410078.85208.930210098.86207.522910118.94210.434810128.98212.8024
10149.13214.548510159.27215.890610179.57219.900210230.31220.572110240.17221.7568
#Mann= 3 , 0 , 0
9682.045    0.04       09682.045    0.04       010240.17    0.04       0
#XS Ineff= 2 , 0
       0                               0
Bank Sta=9682.045,10240.17
Exp/Cntr=0.3,0.1

Type RM Length L Ch R = 3 ,7334.775,,,
BEGIN DESCRIPTION:
END DESCRIPTION:
Bridge Culvert--1,0,-1,-1, 0
Deck Dist Width WeirC Skew NumUp NumDn MinLoCord MaxHiCord MaxSubmerge Is_Ogee
46.916500,40.000000,2.6,0, 34, 34, , , 0.95, 0, 0,0,,
 9801.98 9809.93 9819.94 9829.94 9839.95 9849.96 9859.96 9869.97 9879.98 9889.99
 9899.99 9910.00 9920.01 9928.61 9981.04 9981.0410096.0410096.0410139.1610140.17
10148.9410150.1810160.1810170.1810180.1910190.1910200.2010210.2010220.2110230.21
10240.2110250.2210260.2210260.99
  224.43  223.77  223.21  223.08  222.80  222.49  222.17  221.78  221.34  220.88
  220.46  220.26  220.52  220.72  220.58  220.58  220.27  220.27  220.16  220.15
  220.08  220.07  220.15  220.28  220.56  220.84  221.07  221.34  221.82  222.50
  222.80  227.32  229.69  229.75
 -775.57 -776.23 -776.79 -776.92 -777.20 -777.51 -777.83 -778.22 -778.66 -779.12
 -779.54 -779.74 -779.48 -779.28 -779.42  213.58  213.27 -779.73 -779.84 -779.85
 -779.92 -779.93 -779.85 -779.72 -779.44 -779.16 -778.93 -778.66 -778.18 -777.50
 -777.20 -772.68 -770.31 -770.25
 9801.98 9809.93 9819.94 9829.94 9839.95 9849.96 9859.96 9869.97 9879.98 9889.99
 9899.99 9910.00 9920.01 9928.61 9969.87 9969.8710084.8710084.8710139.1610140.17
10148.9410150.1810160.1810170.1810180.1910190.1910200.2010210.2010220.2110230.21
10240.2110250.2210260.2210260.99
  224.43  223.77  223.21  223.08  222.80  222.49  222.17  221.78  221.34  220.88
  220.46  220.26  220.52  220.72  220.61  220.61  220.30  220.30  220.16  220.15
  220.08  220.07  220.15  220.28  220.56  220.84  221.07  221.34  221.82  222.50
  222.80  227.32  229.69  229.75
 -775.57 -776.23 -776.79 -776.92 -777.20 -777.51 -777.83 -778.22 -778.66 -779.12
 -779.54 -779.74 -779.48 -779.28 -779.39  213.61  213.30 -779.70 -779.84 -779.85
 -779.92 -779.93 -779.85 -779.72 -779.44 -779.16 -778.93 -778.66 -778.18 -777.50
 -777.20 -772.68 -770.31 -770.25
BR Coef=-1 , 0 , 0 ,, 0 ,,,0.8,0,1,0,
WSPro=,,,, 1 ,,,, 0 ,,,, 0 ,,,,-1 ,-1 ,-1 , 0 , 0 , 0 , 0 , 0
BC Design=,, 0 ,, 0 ,,,,,,

Type RM Length L Ch R = 1 ,7267.248,497.708000,497.708000,497.708000
XS GIS Cut Line= 6
 807759.78487888796833.239693463807724.403786212796965.114675239
807654.005884629797109.748267195807652.842459724797141.228481477
807673.098493792797265.912974816807670.981330242797399.810436316
#Sta/Elev= 30
9636.129233.81529679.366233.0704 9689.72233.85059710.427238.65559720.781237.6986
9741.488230.23589751.842 227.2029762.196225.08219770.367224.23739817.005223.5459
9839.855219.23569883.757216.9164    9906214.16399933.524212.12799948.259211.8604
9968.972212.66279977.719208.42379989.273202.02759999.451201.010510009.63 201.874
10019.81205.121210040.16206.890710060.45207.291110080.56206.433610090.62207.4151
10120.66214.608910130.67215.606810180.69 224.38710190.69224.956410225.61223.5858
#Mann= 3 , 0 , 0
9636.129  0.0503       09636.129  0.0503       010225.61  0.0503       0
#XS Ineff= 2 , 0
       0                               0
Bank Sta=9636.129,10225.61
Exp/Cntr=0.3,0.1

Type RM Length L Ch R = 1 , 6769.54,334.859700,334.859700,334.859700
XS GIS Cut Line= 6
807618.792960851796801.573292456807559.716996958796887.172168318
807524.589950739796922.306965442807457.255196005796975.643080839
807346.603352647797133.283514015807270.390164381797258.259857236
#Sta/Elev= 30
9814.967227.36739841.749229.61489853.963234.70969860.683233.87979878.266227.8453
9888.084226.47569916.352226.52689939.963 222.6589954.107222.17259958.498 220.766
9968.251214.95889973.146209.07849981.104201.93959993.903197.6403    9999197.6145
10006.41197.9449 10022.9203.267610128.44203.148510164.06205.867510225.15213.6756
 10261.5212.713810273.46211.059410286.86207.497710297.38206.301510309.07 209.532
10320.65214.401910332.23216.144910345.13217.167110366.98216.467410393.91217.9863
#Mann= 3 , 0 , 0
9814.967    0.04       09814.967    0.04       010393.91    0.04       0
#XS Ineff= 2 , 0
       0                10255.52       0
Bank Sta=9814.967,10393.91
Exp/Cntr=0.3,0.1

Type RM Length L Ch R = 1 ,6434.681,162.848400,162.848400,162.848400
XS GIS Cut Line= 5
807371.902195632796778.111083642807302.457751244 796908.31941697
 807281.59303841796954.519852594807228.203074425797108.110579401
807184.402195632797234.708305851
#Sta/Elev= 30
 9703.09229.44169710.897229.00449733.564 225.2229767.564223.99239778.897224.1953
 9790.23227.53719801.564228.59629812.897225.4184 9824.23223.10459857.989219.4718
9879.934215.80839890.907 212.6039901.861207.86849912.448205.13579923.035203.6571
9965.382 200.8699975.969198.21369986.556 191.5839997.143191.556210007.73191.9519
10018.32194.5733 10028.9198.680710060.66204.394410071.25206.858210081.83  207.82
10104.34 208.28610124.16215.5285 10155.9218.205710187.65218.714410197.92219.7164
#Mann= 3 , 0 , 0
 9703.09  0.0436       0 9703.09  0.0436       010197.92  0.0436       0
#XS Ineff= 2 , 0
       0                               0
Bank Sta=9703.09,10197.92
Exp/Cntr=0.3,0.1

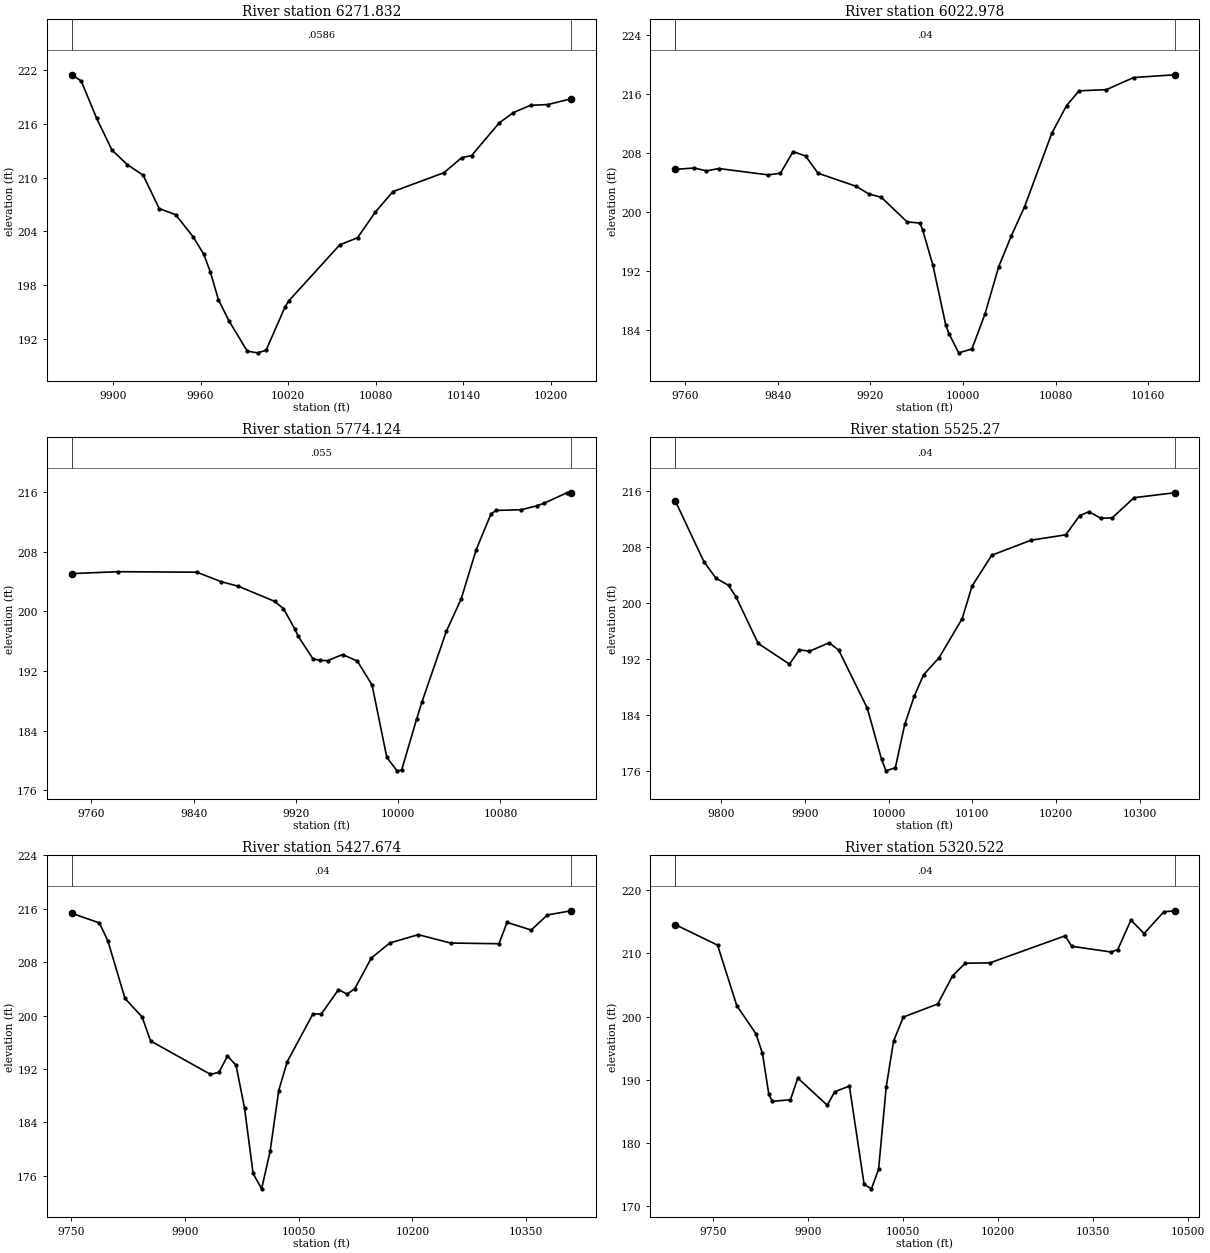
Type RM Length L Ch R = 1 ,6271.832,248.854000,248.854000,248.854000
XS GIS Cut Line= 6
807166.586475858796858.907725985807154.468001956796897.330435259
 807131.18755331796941.501480319807083.874418266797000.529591019
807053.063419748797045.658604157806988.943909242797148.537416849
#Sta/Elev= 30
9871.884221.49959878.273220.79289888.758216.65779899.244213.10119909.729 211.473
9920.632210.28399931.661206.55679942.872205.87459954.834 203.4139962.179201.4493
9966.615199.50479972.241196.36569979.296194.04929991.977190.6252    9999190.4387
10004.81190.718310017.74195.5232 10020.3196.229110055.36202.508410067.46203.2896
10079.57206.143610091.68208.444910126.63210.559110138.84212.238610145.54212.4684
10164.44216.109810174.19217.276510185.97 218.09210197.75218.1701 10213.7218.8153
#Mann= 3 , 0 , 0
9871.884  0.0586       09871.884  0.0586       0 10213.7  0.0586       0
#XS Ineff= 2 , 0
       0                               0
Bank Sta=9871.884,10213.7
Exp/Cntr=0.3,0.1

Type RM Length L Ch R = 1 ,6022.978,248.854000,248.854000,248.854000
XS GIS Cut Line= 6
806996.344200952796629.734253799806954.012348101796742.325356938
 806931.65891686796793.005619787806900.147344447796857.512805928
 806873.26004183796906.554736669806805.600420185 797014.95858912
#Sta/Elev= 30
9751.506205.78789767.698205.97519778.305205.57839788.912205.90249831.623205.0431
  9842.2205.2603 9853.16208.19129863.928207.5978 9874.74205.26479907.528203.5064
9918.458202.47659929.427202.00389951.686198.68469962.815198.52619965.161197.5647
9973.945192.83639985.074184.73469987.944183.53669996.203180.979110007.63181.4939
10018.83186.175710030.78192.616910041.71196.800810053.16200.744410076.68210.6632
10089.42214.416610100.25216.407410123.83216.570510147.41218.205910182.72218.5784
#Mann= 3 , 0 , 0
9751.506    0.04       09751.506    0.04       010182.72    0.04       0
#XS Ineff= 2 , 0
       0                               0
Bank Sta=9751.506,10182.72
Exp/Cntr=0.3,0.1

Type RM Length L Ch R = 1 ,5774.124,248.854000,248.854000,248.854000
XS GIS Cut Line= 6
806806.548684534796534.381532353806722.849112482796669.084453075
806675.047585644796751.825561882806674.022628018796753.542961621
 806629.84213796796827.185198105806603.221169923796867.510849657
#Sta/Elev= 30
9744.854205.04379780.902205.29469842.526205.22969861.473203.96159875.088203.3426
9903.443201.31579910.275 200.3529919.134197.62229921.824 196.6469933.373193.6107
9939.124193.41759944.922193.38239956.471194.19819968.019 193.3299979.568190.1219
9991.117180.43419999.093178.6169 10002.7178.715210014.36185.504110018.54187.8105
10037.68197.300210049.35201.685110061.01208.232810072.67213.070410076.85 213.504
10096.24 213.59710108.22214.111210113.82214.447210131.97215.8677 10135.2215.7977
#Mann= 3 , 0 , 0
9744.854   0.055       09744.854   0.055       0 10135.2   0.055       0
#XS Ineff= 2 , 0
       0                               0
Bank Sta=9744.854,10135.2
Exp/Cntr=0.3,0.1

Type RM Length L Ch R = 1 , 5525.27,97.596500,97.596500,97.596500
XS GIS Cut Line= 6
806707.320406257796430.738910383806603.485052558 796521.35485694
806448.381965343 796606.16970733806357.239659485796667.403392086
806283.591527213796739.737735886806241.624269871 796793.15522896
#Sta/Elev= 30
9745.305214.5834 9779.33205.93269793.604203.59919808.822202.55099817.814200.8803
9844.134194.26189881.505191.31149893.459193.35869905.326193.14669928.992194.3593
9940.419  193.299974.481185.00949991.481 177.7259996.796176.067110007.98176.5123
10019.21182.689910030.44186.689910041.67189.778110060.32192.235410087.85197.8142
10099.63202.458610123.17206.866110170.24209.014910211.58209.783210228.17212.5214
10239.29213.081510253.14212.151110266.99212.203810293.09215.0846 10341.5215.7844
#Mann= 3 , 0 , 0
9745.305    0.04       09745.305    0.04       0 10341.5    0.04       0
#XS Ineff= 2 , 0
       09922.468                       0
Bank Sta=9745.305,10341.5
Exp/Cntr=0.3,0.1

Type RM Length L Ch R = 1 ,5427.674,107.151900,107.151900,107.151900
XS GIS Cut Line= 3
806687.145979643796374.046398342806284.535135627796581.845543638
806214.875194877796774.295888424
#Sta/Elev= 30
9751.307215.29669787.482213.87659798.736211.16239821.242202.55559843.749199.7922
9855.003196.18869933.776191.1978 9945.03191.48229956.283 193.9419967.537192.5637
 9978.79186.12989990.043176.3431 10001.3174.042310012.55179.7051 10023.8188.7602
10035.06193.096210068.82200.218210080.07  200.2410102.58203.886910113.83203.1995
10124.04 204.01710145.85 208.608 10170.1210.861410207.74212.114910250.28210.8585
10314.09210.754110324.72 213.94810356.62212.807710377.89215.062710409.05215.6899
#Mann= 3 , 0 , 0
9751.307    0.04       09751.307    0.04       010409.05    0.04       0
#XS Ineff= 2 , 0
       0                               0
Bank Sta=9751.307,10409.05
Exp/Cntr=0.3,0.1

Type RM Length L Ch R = 1 ,5320.522,292.959700,292.959700,292.959700
XS GIS Cut Line= 4
806710.759518921796332.722704649806559.632867783796309.109165415
 806256.19888857796489.752740607806179.454886019796761.308441833
#Sta/Elev= 30
9690.129214.52229756.687 211.2879787.051201.72079817.415197.26379827.536194.1737
9837.658187.7019 9843.09 186.5979871.757  186.859883.395190.27859929.947 185.983
9941.585188.10869964.861 189.0139988.137 173.4779999.775 172.769   10011175.8931
10023.05188.871710034.69196.133610050.09199.919410104.52201.998210127.79 206.424
10147.84  208.4310186.93208.487410305.59212.761310315.99211.104710378.34210.2034
10388.73 210.57810409.51215.246510430.29213.123310461.47216.553210478.42216.7195
#Mann= 3 , 0 , 0
9690.129    0.04       09690.129    0.04       010478.42    0.04       0
#XS Ineff= 2 , 0
       09954.735                       0
Bank Sta=9690.129,10478.42
Exp/Cntr=0.3,0.1

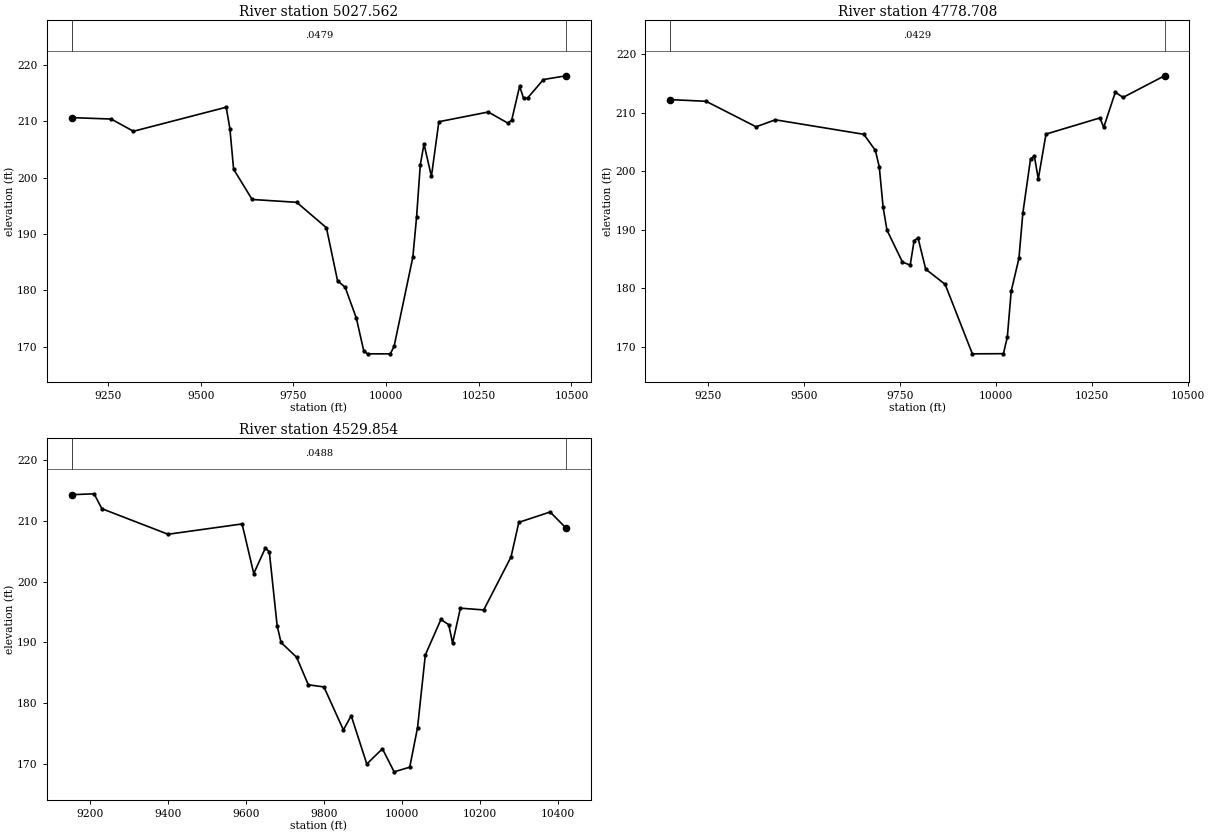
Type RM Length L Ch R = 1 ,5027.562,248.854000,248.854000,248.854000
XS GIS Cut Line= 6
806154.002023759795488.671713233806137.846692781796055.953987871
806148.849805527796205.272649563806186.061303222796460.848227273
806166.308337934796579.555598769806085.283141165  796802.0584823
#Sta/Elev= 30
9152.124210.60069258.541210.34989318.592208.18419568.776212.44069578.777208.6433
9588.778201.46839638.784196.11019758.842195.60789839.089191.10869869.238181.6887
 9889.47180.59539919.819175.09939940.087169.22649950.274168.781210011.39168.7812
10021.56 170.08810072.19185.889910082.26192.991210092.27202.235810102.28205.9306
 10122.3200.185410142.35209.873610275.55211.594610328.15209.6409 10338.8210.1558
 10360.2216.158610370.89214.006710381.59214.067410424.38217.344310485.66218.0085
#Mann= 3 , 0 , 0
9152.124  0.0479       09152.124  0.0479       010485.66  0.0479       0
#XS Ineff= 2 , 0
       09937.014        10024.54       0
Bank Sta=9152.124,10485.66
Exp/Cntr=0.3,0.1

Type RM Length L Ch R = 1 ,4778.708,248.854000,248.854000,248.854000
XS GIS Cut Line= 6
805865.402577604795531.341304227805870.305948355795819.284806313
805879.956540436796011.463465684805944.026409857796545.159197257
805940.600516898 796675.63546401 805919.76834785796811.484153897
#Sta/Elev= 30
9152.124212.21999245.796211.93049375.815207.57399425.822208.76799656.154206.2892
9686.265203.52859696.302200.7113 9706.34193.80189716.377189.90839756.633184.4563
9776.761183.94459786.826188.0767 9796.89188.63399817.092183.24799867.641180.6578
9938.409168.781210019.29168.807710029.39 171.63510039.47179.481710059.63185.0997
 10069.7192.777410089.86202.119510099.92202.506610109.95198.6599   10130206.3257
10270.16209.087610280.18 207.485 10310.3213.471210330.45 212.59610438.36216.2898
#Mann= 3 , 0 , 0
9152.124  0.0429       09152.124  0.0429       010438.36  0.0429       0
#XS Ineff= 2 , 0
       09888.845                       0
Bank Sta=9152.124,10438.36
Exp/Cntr=0.3,0.1

Type RM Length L Ch R = 1 ,4529.854,248.854000,248.854000,248.854000
XS GIS Cut Line= 6
805645.400020735795557.551079284805660.495328641796084.998814445
805683.672142183796484.515068794805685.069732806 796559.42253562
805680.028055354796705.312821771 805667.41294556796825.855190468
#Sta/Elev= 30
9152.098214.23789209.566214.39069229.572211.94399399.626207.75149589.712209.4424
9619.731201.31069649.751205.51989659.757204.83829679.768192.75769689.782190.0051
9729.833187.57469759.871183.05729799.922182.70949849.986175.65819870.012177.9879
9910.103 170.0679950.197172.56419980.267168.781210020.35169.544510040.39176.0192
10060.42  187.9610100.46 193.77110120.46192.921510130.46189.900810150.47195.6273
10210.47 195.33910280.55204.031910300.58209.705310380.94211.400310422.12208.7559
#Mann= 3 , 0 , 0
9152.098  0.0488       09152.098  0.0488       010422.12  0.0488       0
#XS Ineff= 2 , 0
       0                               0
Bank Sta=9152.098,10422.12
Exp/Cntr=0.3,0.1