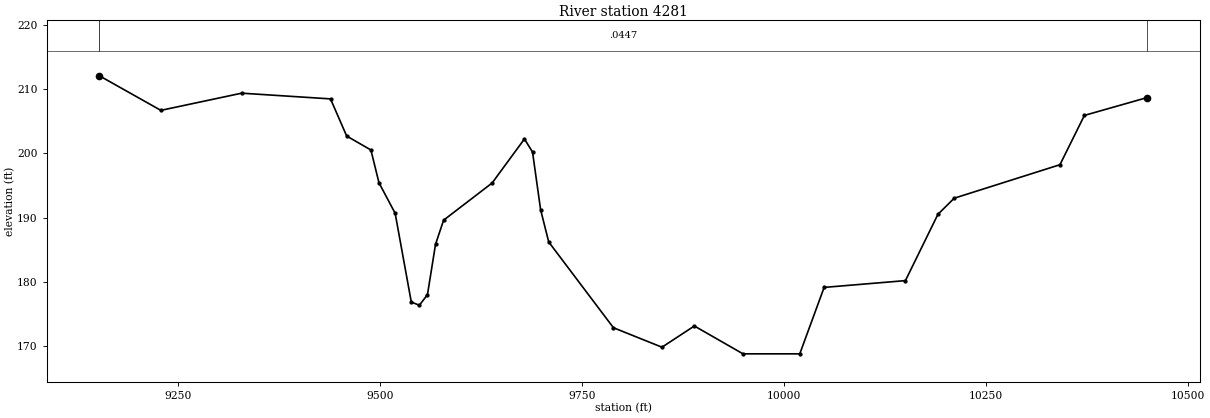
HEC-RAS study 17433_ras.prj: 17433

--- 17433_ras.g01 (geometry) --- (continued)

Type RM Length L Ch R = 1 ,    4281,0.000000,0.000000,0.000000
XS GIS Cut Line= 6
805453.166404582795548.909141469805457.221168268795757.339309266
805456.252267496795939.041913354805450.255455014796126.777087556
 805425.94193421796445.732063766805378.578914704796842.303597686
#Sta/Elev= 30
9152.115212.09349228.221206.7061 9328.24209.38359438.247208.49319458.247202.7094
9488.247200.53329498.248195.41839518.248190.67979538.248176.84339548.251176.3506
9558.256 177.9959568.262 185.8529578.267189.60439638.297195.39129678.318202.2534
9688.323200.21289698.328191.22959708.333186.21249788.453172.84969848.566169.8133
9888.651173.12019948.878168.781210019.16168.7812 10049.3179.130210149.94180.1863
10190.19 190.51510210.32193.022410341.23198.240310371.48205.920610449.44208.7077
#Mann= 3 , 0 , 0
9152.115  0.0447       09152.115  0.0447       010449.44  0.0447       0
#XS Ineff= 2 , 0
       09688.198                       0
Bank Sta=9152.115,10449.44
Exp/Cntr=0.3,0.1